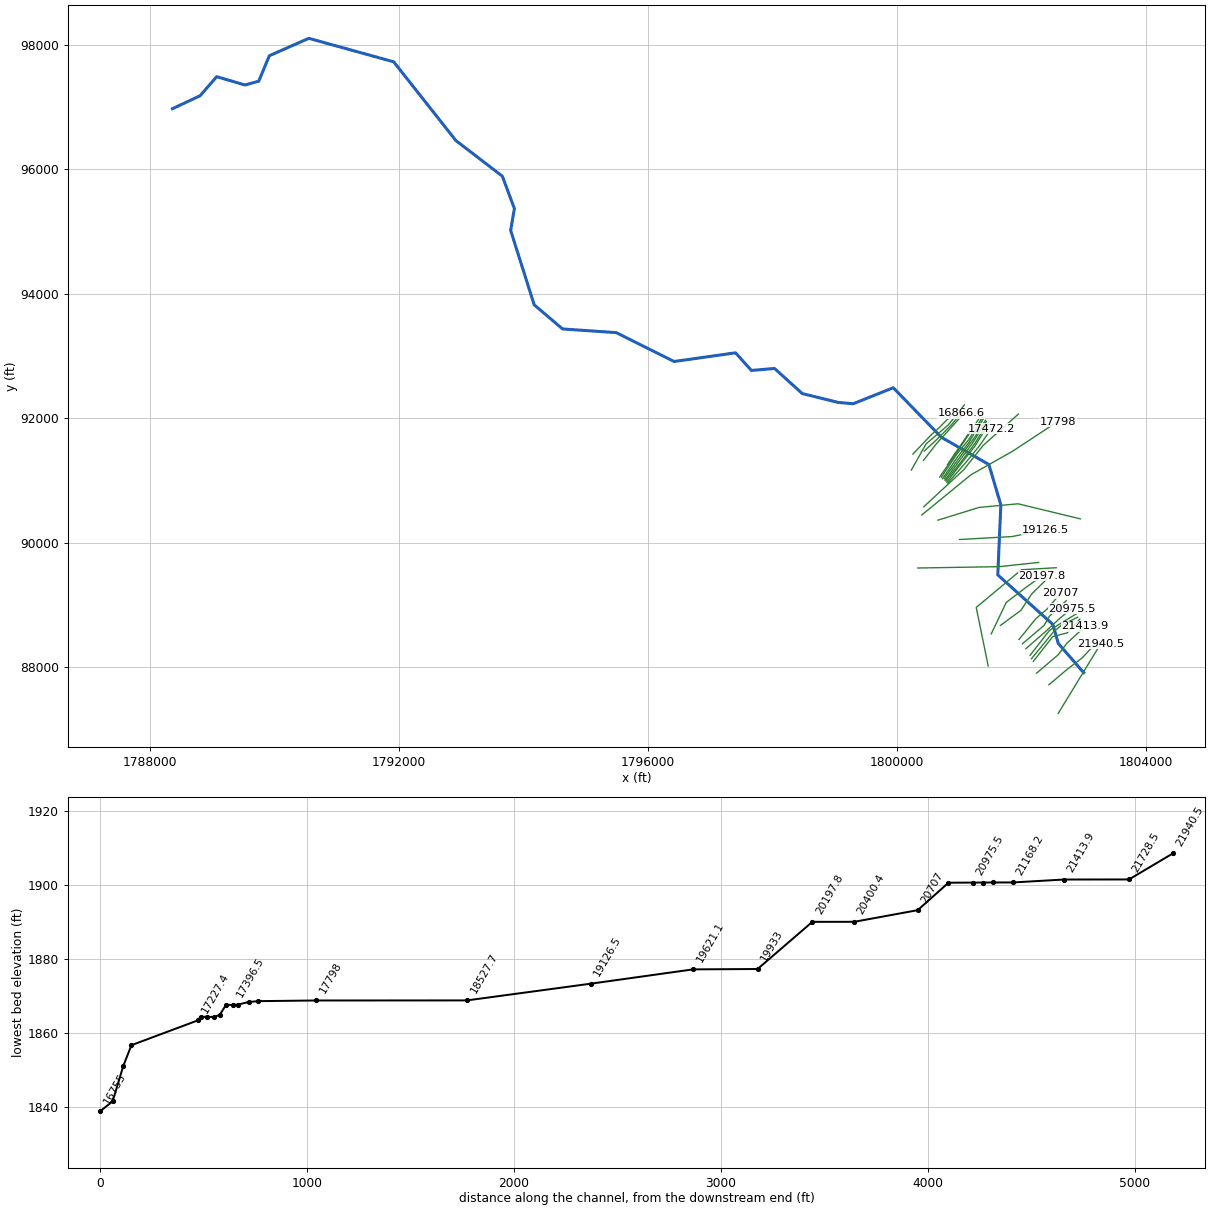
--- Cucumber Creek.prj (project) ---

Proj Title=Cucumber Creek
Current Plan=p01
Default Exp/Contr=0,0
English Units
Geom File=g01
Flow File=f01
Plan File=p01
BEGIN DESCRIPTION:
END DESCRIPTION:
DSS Export Rating Curves= 0
DSS Export Rating Curve Sorted= 0
DSS Export Volume Flow Curves= 0
DXF OffsetX= 0
DXF OffsetY= 0
DXF ScaleX= 0
DXF ScaleY= 0

--- Cucumber Creek.p01 (plan) ---

Plan Title=Floodplain
Program Version=4.00
Geom File=g01
Flow File=f01
K Sum by GR=0
Std Step Tol=0.01
Critical Tol=0.01
Num of Std Step Trials=20
Max Error Tol=0.3
Flow Tol Ratio=0.001
Split Flow NTrial=30
Split Flow Tol=0.02
Split Flow Ratio=0.02
Log Output Level=0
Friction Slope Method=1
Unsteady Friction Slope Method=2
Unsteady Bridges Friction Slope Method=1
Global Log Level=0
CheckData=False
Run HTab=0
Run UNet=0
Run PostProcess=0
UNET Theta=0
UNET Theta Warmup=0
UNET ZTol=0
UNET ZSATol=0
UNET MxIter=0
UNET MaxInSteps=0
UNET DtIC=0
UNET DtMin=0
UNET MaxCRTS=0
UNET WFStab=0
UNET SFStab=0
UNET WFX=0
UNET SFX=0
UNET DSS MLevel=0
UNET DZMax Abort=0
UNET Convert EG Bridges=0
UNET Use Existing IB Tables=0
UNET Froude Limit=0
UNET Froude Power=0
Write IC File=0
Echo Input=False
Echo Output=False
Write Detailed=0

--- Cucumber Creek.f01 (steady flow) ---

Flow Title=NFF Regression Equation
Program Version=4.00
Number of Profiles=1
Profile Names=P100yr
River Rch & RM=Cucumber Creek,Main      ,21940.5
375.6853
River Rch & RM=Cucumber Creek,Main      ,21728.5
612.2710
River Rch & RM=Cucumber Creek,Main      ,19933
658.1779
River Rch & RM=Cucumber Creek,Main      ,19621.1
764.3384
River Rch & RM=Cucumber Creek,Main      ,17798
808.0969
River Rch & RM=Cucumber Creek,Main      ,17518.2
896.5181
River Rch & RM=Cucumber Creek,Main      ,16905.9
903.3051
River Rch & RM=Cucumber Creek,Main      ,15733.6
1002.403
River Rch & RM=Cucumber Creek,Main      ,13283.8
1074.676
River Rch & RM=Cucumber Creek,Main      ,12482.8
1191.767
River Rch & RM=Cucumber Creek,Main      ,9240.7
1286.407
River Rch & RM=Cucumber Creek,Main      ,6525.4
1418.371
River Rch & RM=Cucumber Creek,Main      ,4152.3
1546.472
River Rch & RM=Cucumber Creek,Main      ,261.6
1640.542
Boundary for River Rch & Prof#=Cucumber Creek,Main      ,1
Up Type=0
Dn Type=3
Dn Slope=0.015868

--- Cucumber Creek.g01 (geometry) ---

Geom Title=USGS 10m DEM
Program Version=4.00

River Reach=Cucumber Creek  ,Main
Reach XY= 30
     1802999.108       87916.165     1802590.339        88386.25
     1802503.082       88691.255     1801617.939       89486.783
     1801667.464       90610.898      1801474.87       91259.427
     1800711.572       91697.281     1799938.841       92492.809
     1799296.602       92235.756     1799053.998        92256.85
     1798477.039       92398.864     1798031.222       92802.163
     1797658.805       92770.537     1797404.897       93053.459
     1796416.698       92914.309     1795487.018       93377.971
      1794624.84       93436.909     1794168.905       93824.454
     1793790.794       95019.318     1793850.537       95371.488
     1793657.157       95890.311     1792910.368       96462.588
     1791911.752       97727.092     1790547.105       98104.312
     1789912.988        97824.89     1789743.191       97416.121
     1789520.845        97355.42      1789067.15       97488.442
      1788801.45       97182.651     1788355.867       96973.898

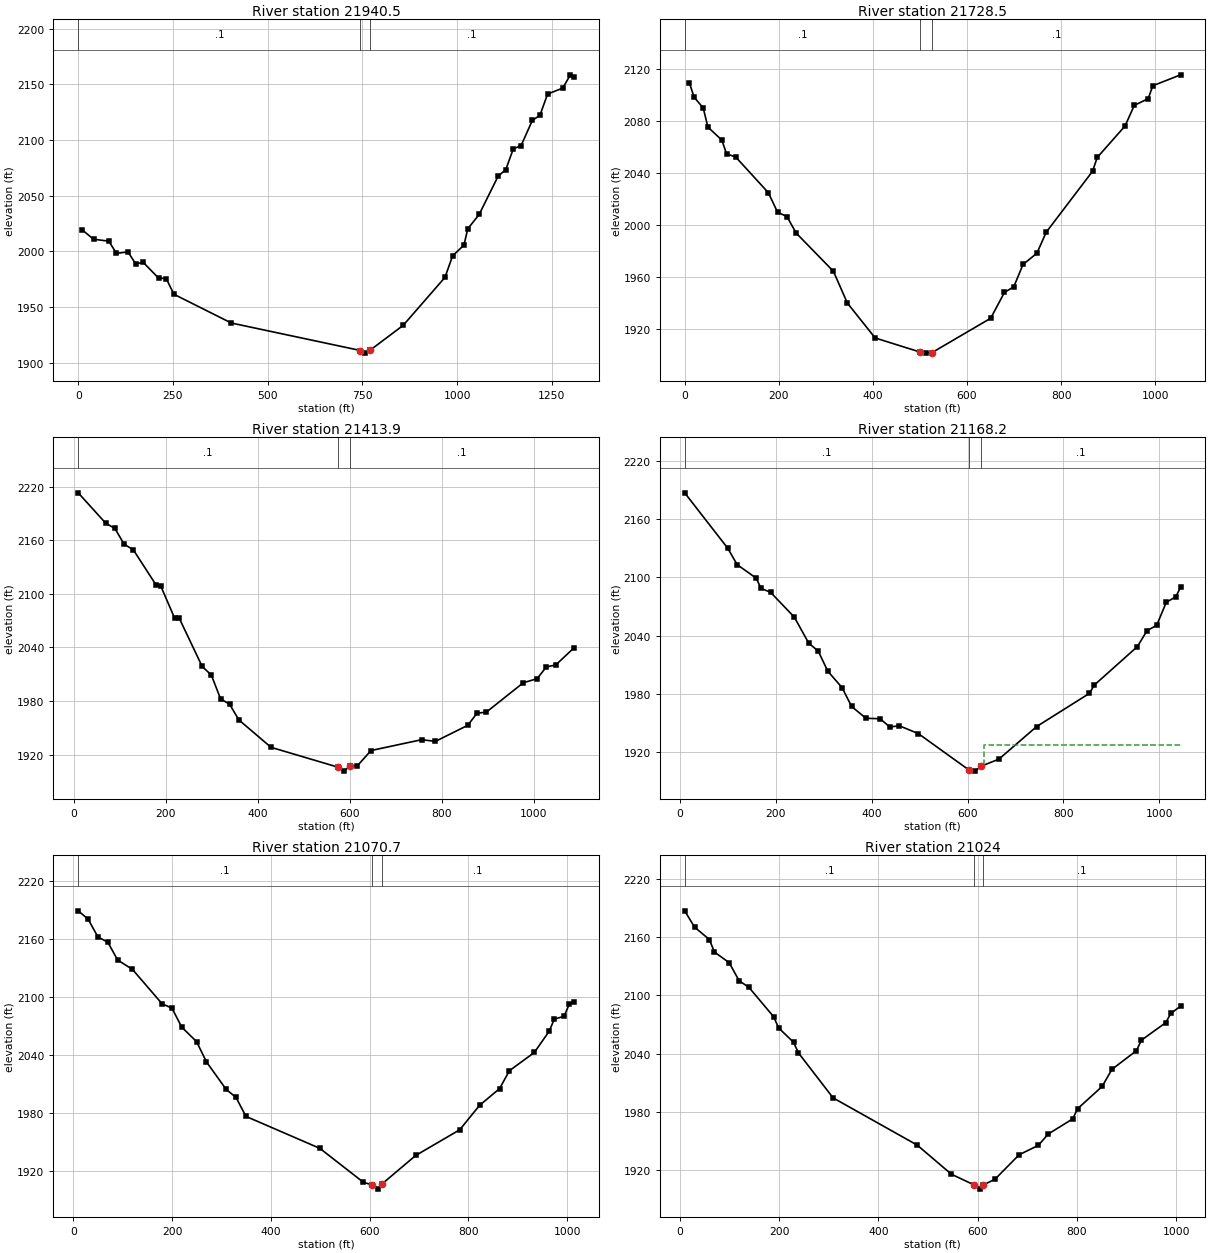
Type RM Length L Ch R = 1 ,21940.5 ,222,212.1,202.2
XS GIS Cut Line= 3
     1802589.365       87262.971      1802989.29       87918.066
     1803271.613        88380.11
#Sta/Elev= 30
    10.1 2019.49    40.4 2010.97    80.8 2009.24     101 1998.19   131.3 1999.65
   151.5 1988.91   171.7 1990.14   212.1 1976.05   232.3 1975.67   252.5 1961.54
     404  1935.7   744.9    1911   757.4 1908.64   769.9 1911.13   857.8 1933.61
   968.1 1976.73   988.1 1995.96  1018.2 2005.76  1028.2 2020.34  1058.3 2033.22
  1108.4  2067.7  1128.5 2073.51  1148.6 2092.34  1168.6 2094.82  1198.7 2117.76
  1218.7 2122.28  1238.8 2141.38  1278.9 2146.76    1299 2158.67    1309 2156.56
#Mann= 3 , 0 , 0
       0      .1       0   744.9    .045       0   769.9      .1       0
Bank Sta=744.9,769.9
XS Rating Curve= 0 ,0
Exp/Cntr=0.3,0.1

Type RM Length L Ch R = 1 ,21728.5 ,306.9,314.5,322.2
XS GIS Cut Line= 4
     1802439.573       87722.715     1802741.662       87977.333
     1802975.968       88155.637     1803225.006       88421.836
#Sta/Elev= 30
     9.9 2109.64    19.8  2098.5    39.5 2089.95    49.4 2075.32      79 2065.37
    88.9  2054.9   108.6  2052.3   177.8 2024.94   197.5 2009.84   217.3 2006.62
     237 1993.87   316.1 1964.51   345.7  1940.1   404.9 1913.24   500.4 1902.42
   512.9  1901.6   525.4 1901.96   650.3  1928.4   679.7 1948.33   699.4 1952.57
   719.1 1969.77   748.6  1978.4   768.3 1994.51   866.9 2041.45   876.7 2051.99
   935.8 2076.16   955.5 2092.02   985.1 2097.28   994.9 2107.14    1054 2115.54
#Mann= 3 , 0 , 0
       0      .1       0   500.4    .045       0   525.4      .1       0
Bank Sta=500.4,525.4
XS Rating Curve= 0 ,0
Exp/Cntr=0.3,0.1

Type RM Length L Ch R = 1 ,21413.9 ,265.5,245.8,226.1
XS GIS Cut Line= 4
     1802241.057       87908.284     1802590.493       88205.569
     1802726.308       88387.321     1803022.174       88659.192
#Sta/Elev= 30
      10 2213.12    69.8  2179.1    89.8 2173.19   109.7 2155.62   129.7 2149.36
   179.5 2109.65   189.5 2108.66   219.4 2072.88   229.4 2072.88   279.3 2018.74
   299.2 2009.19   319.2 1982.57   339.1 1976.35     359 1958.92   428.9 1928.24
   574.5 1905.98     587 1901.58   599.5 1906.82   616.6 1907.63   646.2 1924.63
     756 1936.75   786.1  1934.9   856.4 1952.88   876.5 1966.46   896.6 1967.56
     977 2000.51  1007.1 2005.08  1027.2 2018.35  1047.3 2020.31  1087.5 2039.75
#Mann= 3 , 0 , 0
      10      .1       0   574.5    .045       0   599.5      .1       0
Bank Sta=574.5,599.5
XS Rating Curve= 0 ,0
Exp/Cntr=0.3,0.1

Type RM Length L Ch R = 1 ,21168.2 ,84.7,97.5,110.2
XS GIS Cut Line= 4
      1802189.27       88098.169     1802502.613       88497.172
       1802732.3       88555.093     1802935.863       88775.713
#Sta/Elev= 30
     9.9 2186.98    99.5 2130.15   119.4 2113.11   159.2 2099.19   169.1 2088.67
     189 2084.73   238.7 2059.08   268.6 2032.42   288.5  2024.2   308.4 2003.58
   338.2 1986.67   358.1 1967.28     388 1955.15   417.8 1954.64   437.7 1946.17
   457.6 1947.44   497.4 1939.35   603.4 1901.78   615.9 1900.79   628.4 1905.89
   665.3  1913.1   744.2 1946.67   854.3  1980.8   864.3 1989.27   954.3 2028.89
   974.4 2045.33   994.4 2050.64  1014.4 2074.32  1034.4 2080.13  1044.4 2089.98
#Mann= 3 , 0 , 0
     9.9      .1       0   603.4    .045       0   628.4      .1       0
#XS Ineff= 2 , 0
                          633.34         1928.06
Permanent Ineff=
       F       F
Bank Sta=603.4,628.4
XS Rating Curve= 0 ,0
Exp/Cntr=0.3,0.1

Type RM Length L Ch R = 1 ,21070.7 ,50.8,46.7,42.6
XS GIS Cut Line= 4
     1802159.081       88139.659     1802506.607       88565.079
     1802638.428       88676.927     1802900.071        88806.75
#Sta/Elev= 30
      10 2189.48      30 2180.85    49.9  2162.4    69.9  2156.9    89.9 2138.47
   119.9 2128.69   179.8 2093.06   199.8 2088.53   219.7 2068.79   249.7 2053.79
   269.7 2032.76   309.6 2004.25   329.6 1995.89   349.6 1976.27   499.4 1943.05
   587.7 1907.79   604.1 1905.41   616.6 1900.78  624.37  1905.8   693.4 1935.68
   782.6 1962.36   822.9 1987.77   863.2 2005.02   883.3 2023.66   933.7 2042.56
   963.9 2064.66     974 2077.09   994.1 2080.16  1004.2 2092.53  1014.3 2095.15
#Mann= 3 , 0 , 0
      10      .1       0   604.1    .045       0  624.37      .1       0
Bank Sta=604.1,624.37
XS Rating Curve= 0 ,0
Exp/Cntr=0.3,0.1

Type RM Length L Ch R = 1 ,21024   ,43.5,48.5,53.6
XS GIS Cut Line= 4
     1802137.111       88195.583     1802449.766       88596.246
     1802639.601       88715.247     1802876.104       88858.679
#Sta/Elev= 30
      10 2186.96    29.9 2170.21    59.8 2157.42    69.8 2144.64    99.7 2133.59
   119.6  2115.1   139.5 2108.23   189.3 2077.95   199.3 2066.49   229.2 2051.83
   239.2 2040.83   308.9 1994.62   478.3 1946.06   547.2 1916.11   593.1 1905.07
   605.6 1900.77  609.92 1904.73   634.9 1910.88   683.6  1936.1   722.5 1945.81
   742.1 1957.39   791.5 1972.98   801.4 1983.46   850.8 2006.34   870.6 2023.99
     920 2043.15   929.8 2053.88   979.2 2072.04   989.1  2081.5  1008.9  2088.9
#Mann= 3 , 0 , 0
      10      .1       0   593.1    .045       0  609.92      .1       0
Bank Sta=593.1,609.92
XS Rating Curve= 0 ,0
Exp/Cntr=0.3,0.1

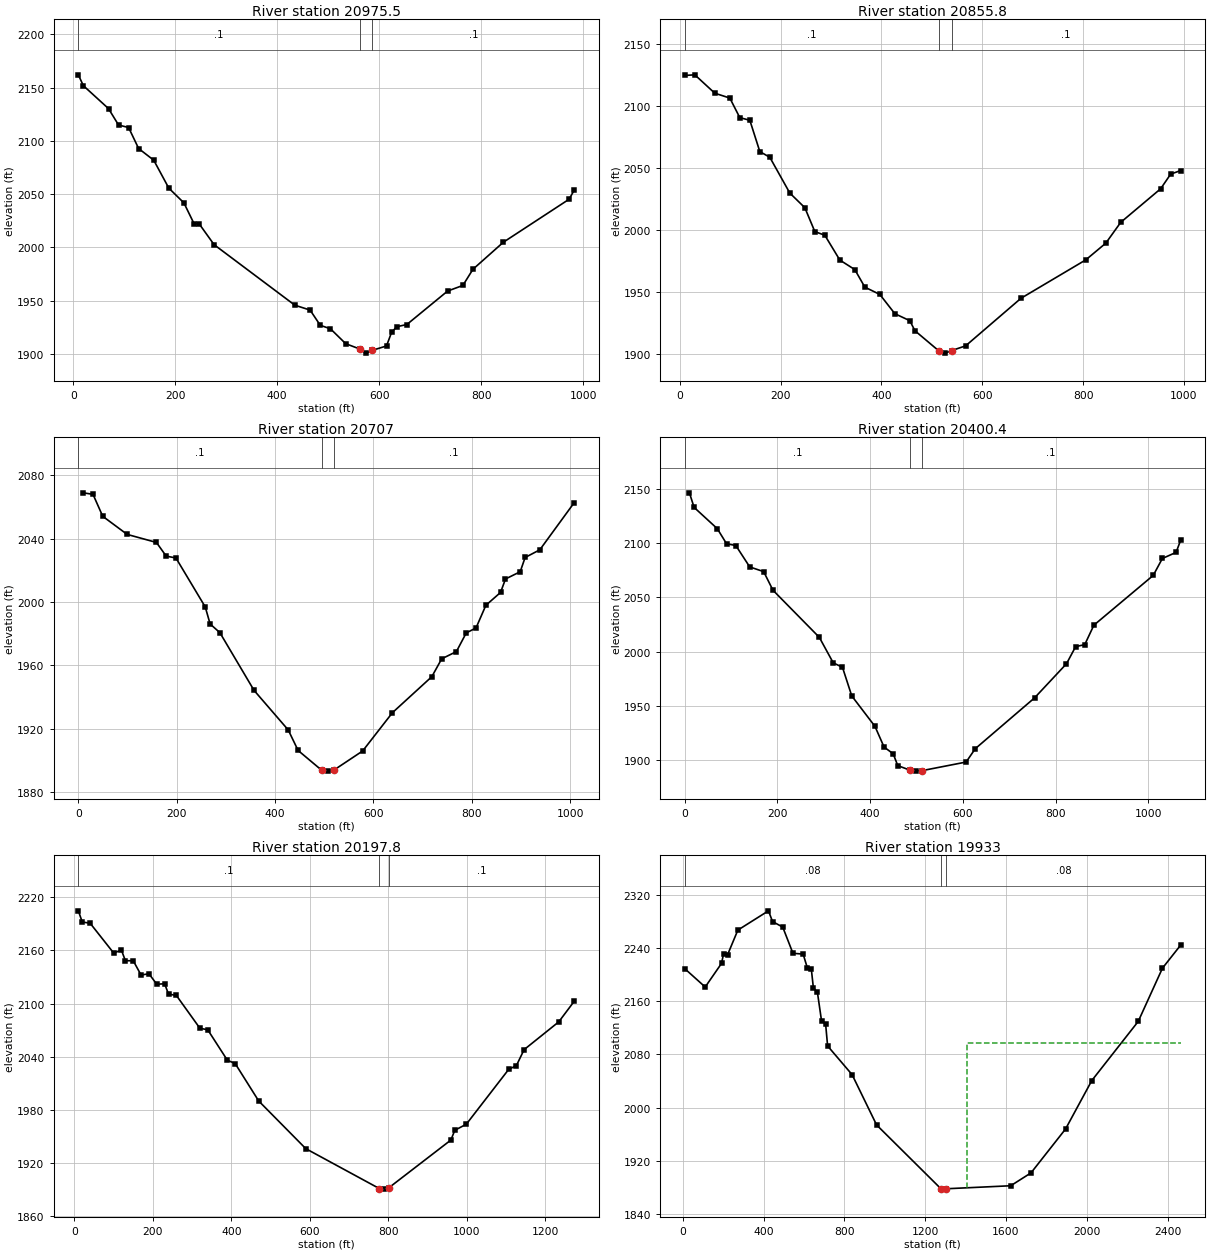
Type RM Length L Ch R = 1 ,20975.5 ,111.1,119.6,128.1
XS GIS Cut Line= 4
     1802068.434          88301.     1802366.208       88559.934
     1802638.184       88810.165     1802810.711        88944.02
#Sta/Elev= 30
     9.9 2162.04    19.7 2151.88    69.1 2130.32    88.8  2114.9   108.5 2112.58
   128.2 2092.82   157.8 2081.91   187.4 2055.66     217 2041.81   236.8 2022.35
   246.6 2022.35   276.2 2002.59   434.6 1945.75   464.5 1941.18   484.5 1926.87
   504.5 1923.58   534.4  1909.6   561.9 1904.64   574.4 1900.75   586.9 1903.43
   614.4 1907.49   624.3 1920.17   634.3 1925.52   654.3 1927.61   734.2 1959.01
   764.2  1964.3     784  1979.5   843.6 2004.86   972.6 2045.24   982.5 2053.72
#Mann= 3 , 0 , 0
     9.9      .1       0   561.9    .045       0   586.9      .1       0
Bank Sta=561.9,586.9
XS Rating Curve= 0 ,0
Exp/Cntr=0.3,0.1

Type RM Length L Ch R = 1 ,20855.8 ,158.2,148.8,139.5
XS GIS Cut Line= 4
     1802015.277        88381.33     1802362.803       88676.927
     1802448.686       88824.725     1802718.319       89072.388
#Sta/Elev= 30
     9.9 2124.89    29.8 2125.38    69.4 2110.54    99.2 2106.63     119 2090.81
   138.9  2088.7   158.7 2063.41   178.5 2058.83   218.2 2029.93     248 2018.11
   267.8 1998.82   287.6  1995.9   317.4 1975.84   347.1 1968.16     367 1953.98
   396.7  1948.1   426.5 1932.55   456.2  1926.9   466.3 1918.81   514.1 1902.41
   526.6 1900.72   539.1 1902.81   566.8 1906.56   676.7    1945   805.3 1976.03
   844.9 1989.49   874.5 2006.29   953.7 2033.41   973.5  2045.2   993.3 2048.11
#Mann= 3 , 0 , 0
     9.9      .1       0   514.1    .045       0   539.1      .1       0
Bank Sta=514.1,539.1
XS Rating Curve= 0 ,0
Exp/Cntr=0.3,0.1

Type RM Length L Ch R = 1 ,20707   ,298.4,306.6,314.8
XS GIS Cut Line= 4
     1801958.936       88448.839     1802226.989       88780.785
     1802410.738        88938.57      1802631.83        89195.77
#Sta/Elev= 30
     9.9 2068.96    29.8 2068.02    49.6 2054.15    99.2 2042.72   158.8 2037.64
   178.6 2029.01   198.4 2027.85     258 1996.94   267.9 1986.19   287.7 1980.72
   357.2 1944.28   426.7 1919.29   446.8 1906.34   494.9 1893.82   507.4  1893.3
   519.9 1894.02     578 1906.02   638.6  1930.2   718.7 1952.94   738.7 1964.18
   768.6 1968.76   788.6 1980.53   808.5 1983.67   828.5 1997.96   858.4  2006.1
   868.4 2014.58   898.3 2019.15   908.3 2028.14   938.2    2033    1008 2062.71
#Mann= 3 , 0 , 0
       0      .1       0   494.9    .045       0   519.9      .1       0
Bank Sta=494.9,519.9
XS Rating Curve= 0 ,0
Exp/Cntr=0.3,0.1

Type RM Length L Ch R = 1 ,20400.4 ,212.2,202.7,193.1
XS GIS Cut Line= 4
      1801660.35       88674.742     1801990.754       88918.126
     1802163.376       89181.376     1802409.364       89423.047
#Sta/Elev= 30
      10 2146.27      20  2132.9    70.1 2113.29    90.1 2099.41   110.1 2097.78
   140.1 2078.09   170.2 2073.75   190.2 2056.67   290.3 2013.27   320.3 1989.83
   340.3 1985.67   360.3 1959.37   410.4 1931.34     430 1912.33   449.7 1906.11
   459.6 1895.22   486.4 1890.96   498.9 1890.15   511.4 1890.55   607.1 1898.52
   626.8 1910.78   754.7 1957.53   823.7 1988.98   843.4 2004.69   863.1 2006.57
   882.8 2024.47  1010.9 2070.28  1030.6 2085.85  1060.2 2091.47    1070 2102.58
#Mann= 3 , 0 , 0
       0      .1       0   486.4    .045       0   511.4      .1       0
Bank Sta=486.4,511.4
XS Rating Curve= 0 ,0
Exp/Cntr=0.3,0.1

Type RM Length L Ch R = 1 ,20197.8 ,263.7,264.8,265.9
XS GIS Cut Line= 4
     1801512.957       88540.402     1801754.935         89045.4
     1802065.299       89282.117     1802328.318       89471.491
#Sta/Elev= 30
      10 2204.81      20 2192.15      40 2190.84     100 2157.17     120 2160.23
     130 2148.39     150 2148.39     170 2132.21     190 2133.66     210 2121.85
     230 2122.32     240 2110.67     260 2109.14     320 2072.04     340 2070.31
     390  2035.9     410 2032.11     470 1989.79     590 1935.92   777.7 1890.76
   790.2 1890.14   802.7 1891.96   960.1 1945.67     970 1956.67   999.4 1963.54
  1107.5 2025.57  1127.1 2029.79  1146.7 2047.84  1235.1 2079.27  1274.4 2102.45
#Mann= 3 , 0 , 0
      10      .1       0   777.7    .045       0   802.7      .1       0
Bank Sta=777.7,802.7
XS Rating Curve= 0 ,0
Exp/Cntr=0.3,0.1

Type RM Length L Ch R = 1 ,19933   ,331.1,311.9,293.7
XS GIS Cut Line= 4
      1801464.12       88024.534     1801271.756       88964.483
     1801998.079       89569.752     1802556.497       89602.413
#Sta/Elev= 30
    10.1 2208.88   111.1 2181.33   191.9 2216.87     202 2231.27   222.2 2230.11
   272.7 2266.93   424.2 2295.92   444.4 2279.79   494.9 2271.45   545.4 2232.05
   595.9 2230.87   616.1 2210.63   636.3 2208.38   646.4 2180.44   666.6 2173.22
   686.8 2130.68   706.9 2126.46     717  2092.7   838.2 2049.54   959.4 1973.94
  1278.8 1877.69  1291.3 1877.39  1303.8 1877.93  1623.3 1882.47  1723.8 1901.84
  1894.8 1967.85  2024.8 2040.75  2254.5 2129.64  2374.4 2209.72  2464.3 2244.28
#Mann= 3 , 0 , 0
    10.1     .08       0  1278.8    .045       0  1303.8     .08       0
#XS Ineff= 2 , 0
                         1407.64         2097.05
Permanent Ineff=
       F       F
Bank Sta=1278.8,1303.8
XS Rating Curve= 0 ,0
Exp/Cntr=0.3,0.1

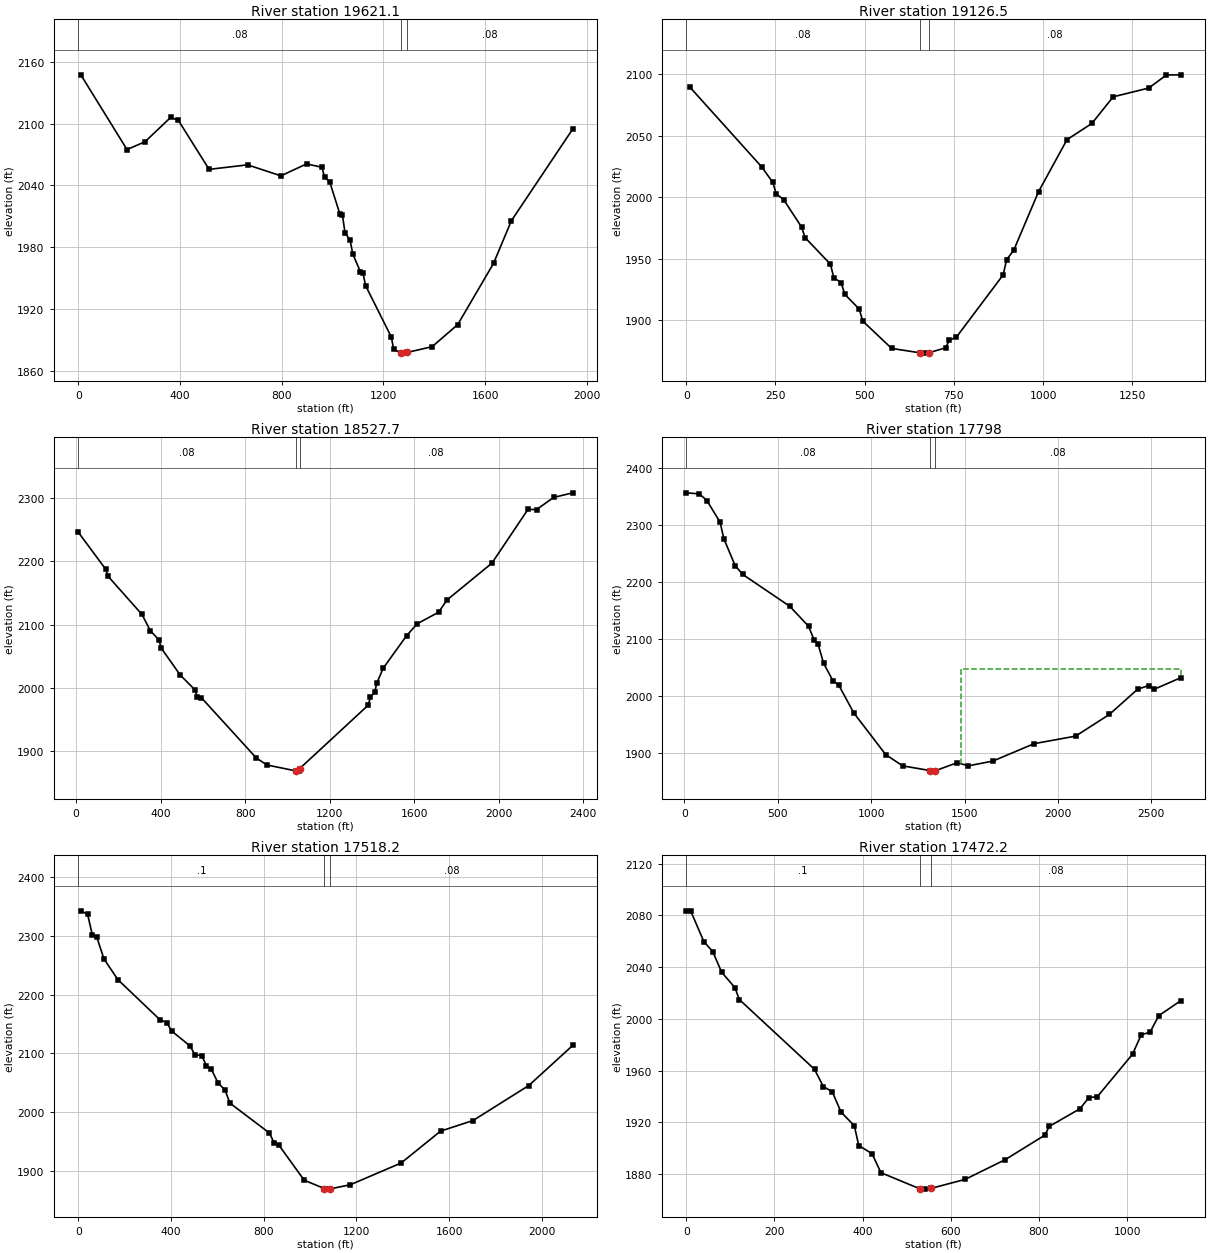
Type RM Length L Ch R = 1 ,19621.1 ,491.9,494.6,496.3
XS GIS Cut Line= 3
     1800334.629       89597.741     1801636.022       89619.167
     1802275.714       89687.167
#Sta/Elev= 30
    10.1 2147.34   191.7 2074.85   262.3 2082.37   363.2 2105.94   393.5 2103.22
   514.6  2055.6   665.9    2060   797.1 2049.32     898  2060.9   958.5 2057.64
   968.6 2048.14   988.8  2043.6  1029.1  2012.2  1039.2 2010.97  1049.3 1993.98
  1069.5 1986.72  1079.6 1973.56  1109.9 1956.17    1120 1954.95    1130 1942.88
  1230.9 1893.15    1241 1880.93  1268.9 1877.48  1281.4 1877.29  1293.9 1877.98
    1392 1883.55  1492.5 1904.99  1633.3 1964.34  1703.6 2005.75  1944.9 2094.75
#Mann= 3 , 0 , 0
       0     .08       0  1268.9    .045       0  1293.9     .08       0
Bank Sta=1268.9,1293.9
XS Rating Curve= 0 ,0
Exp/Cntr=0.3,0.1

Type RM Length L Ch R = 1 ,19126.5 ,597.2,598.8,596.5
XS GIS Cut Line= 3
     1801002.699       90055.395     1801849.622       90102.739
     1802375.662       90213.207
#Sta/Elev= 30
    10.1 2089.36   212.1 2024.37   242.4 2012.06   252.5 2002.66   272.7  1998.1
   323.1 1975.85   333.2 1967.14   403.9 1945.69     414 1934.45   434.2 1930.73
   444.3 1921.18   484.7 1909.22   494.8 1899.42   575.6 1877.25     654 1873.73
   666.5 1873.42     679 1873.67   727.1 1877.73   737.2 1883.89   757.4 1886.46
   888.1 1936.88     898 1949.26   917.9 1956.96   987.6 2004.58  1067.2  2046.7
  1136.9 2059.84  1196.6 2081.44  1296.2 2088.55  1345.9 2099.18  1385.8 2099.29
#Mann= 3 , 0 , 0
       0     .08       0     654    .045       0     679     .08       0
Bank Sta=654,679
XS Rating Curve= 0 ,0
Exp/Cntr=0.3,0.1

Type RM Length L Ch R = 1 ,18527.7 ,730.5,729.8,742.4
XS GIS Cut Line= 4
     1800655.513       90365.758     1801318.323       90570.913
      1801944.31       90628.778     1802943.784         90386.8
#Sta/Elev= 30
    10.1 2246.02   140.8 2187.21   150.8 2176.57   311.7  2116.2   351.9 2090.23
   392.2    2076   402.2 2063.42   492.7 2020.61   563.1 1997.01   573.2 1986.45
   593.3 1984.66   853.5 1889.47   903.4 1878.57  1040.6 1869.25  1053.1  1868.9
 1058.48 1872.97    1383 1973.11  1393.1 1985.91  1413.2 1993.23  1423.3 2007.76
  1453.6 2031.38  1564.5  2082.7  1614.9 2101.58  1715.7 2119.67    1756 2139.17
  1967.7 2196.99  2139.1 2282.08  2179.4 2281.69  2260.1 2300.83  2350.8 2308.17
#Mann= 3 , 0 , 0
    10.1     .08       0  1040.6    .045       0 1058.48     .08       0
Bank Sta=1040.6,1058.48
XS Rating Curve= 0 ,0
Exp/Cntr=0.3,0.1

Type RM Length L Ch R = 1 ,17798   ,267.7,279.7,290.4
XS GIS Cut Line= 4
     1800397.754       90449.924     1801185.344       91093.642
     1801860.143       91475.701      1802582.04       91950.433
#Sta/Elev= 30
    10.1 2356.19    80.6 2354.33   120.9 2342.64   191.4 2304.68   211.5 2275.82
   271.9 2228.77   312.2 2213.34     564 2157.58   664.7 2122.63   694.9 2098.35
   715.1 2092.14   745.3 2057.76   795.6 2027.07   825.8  2019.9   906.4 1971.06
  1077.6 1897.92  1168.2 1878.11  1316.9 1869.77  1329.4 1868.88  1341.9 1869.41
  1460.3 1883.62  1520.7 1878.17  1651.6 1886.51    1873 1917.05    2094 1930.16
  2274.9 1968.13  2425.6 2012.18  2485.9  2018.8    2516 2012.39  2656.6 2032.38
#Mann= 3 , 0 , 0
    10.1     .08       0  1316.9    .045       0  1341.9     .08       0
#XS Ineff= 2 , 0
                          1482.8         2047.97
Permanent Ineff=
       F       F
Bank Sta=1316.9,1341.9
XS Rating Curve= 0 ,0
Exp/Cntr=0.3,0.1

Type RM Length L Ch R = 1 ,17518.2 ,44.6,46,47.5
XS GIS Cut Line= 4
     1800429.316       90581.434     1801071.084       91175.859
     1801381.448       91565.128      1801949.57       92070.125
#Sta/Elev= 30
    10.1 2342.72    40.2 2336.89    60.3 2302.37    80.4 2297.35   110.6 2261.02
   170.9 2225.48   351.9 2157.39   382.1 2152.43   402.2  2138.2   482.6 2112.34
   502.7 2097.64   532.9 2096.18     553 2078.26   573.1 2073.43   603.3 2049.44
   633.4 2037.32   653.6 2015.37   824.5 1964.24   844.6 1947.77   864.7 1943.98
   974.3 1883.97  1061.4 1869.67  1073.9  1868.7  1086.4 1869.12  1173.5 1876.17
  1392.6 1913.21  1562.6 1967.47  1702.7 1985.56  1942.7 2045.04  2132.7 2113.45
#Mann= 3 , 0 , 0
       0      .1       0  1061.4    .045       0  1086.4     .08       0
Bank Sta=1061.4,1086.4
XS Rating Curve= 0 ,0
Exp/Cntr=0.3,0.1

Type RM Length L Ch R = 1 ,17472.2 ,51.8,52.4,53
XS GIS Cut Line= 4
     1800813.061       90961.533     1801072.554       91254.426
     1801321.769       91557.595     1801514.462       91835.073
#Sta/Elev= 30
       0 2083.61      10 2083.61    40.1 2059.74    60.2 2052.08    80.3 2036.19
   110.4 2024.24   120.4 2015.04     291 1961.09     311 1947.73   331.1 1943.85
   351.2 1927.95   381.3 1917.48   391.3 1902.18   421.5 1895.86   441.6 1881.18
   529.8 1868.73   542.3 1868.46   554.8 1868.98   632.8 1876.02   723.4  1891.2
   813.6 1910.22   823.5 1916.98   893.1 1930.59   912.9 1939.08   932.8 1940.06
  1012.3 1972.76  1032.2 1987.83    1052 1989.74  1071.9 2002.56  1121.6 2014.11
#Mann= 3 , 0 , 0
       0      .1       0   529.8    .045       0   554.8     .08       0
Bank Sta=529.8,554.8
XS Rating Curve= 0 ,0
Exp/Cntr=0.3,0.1

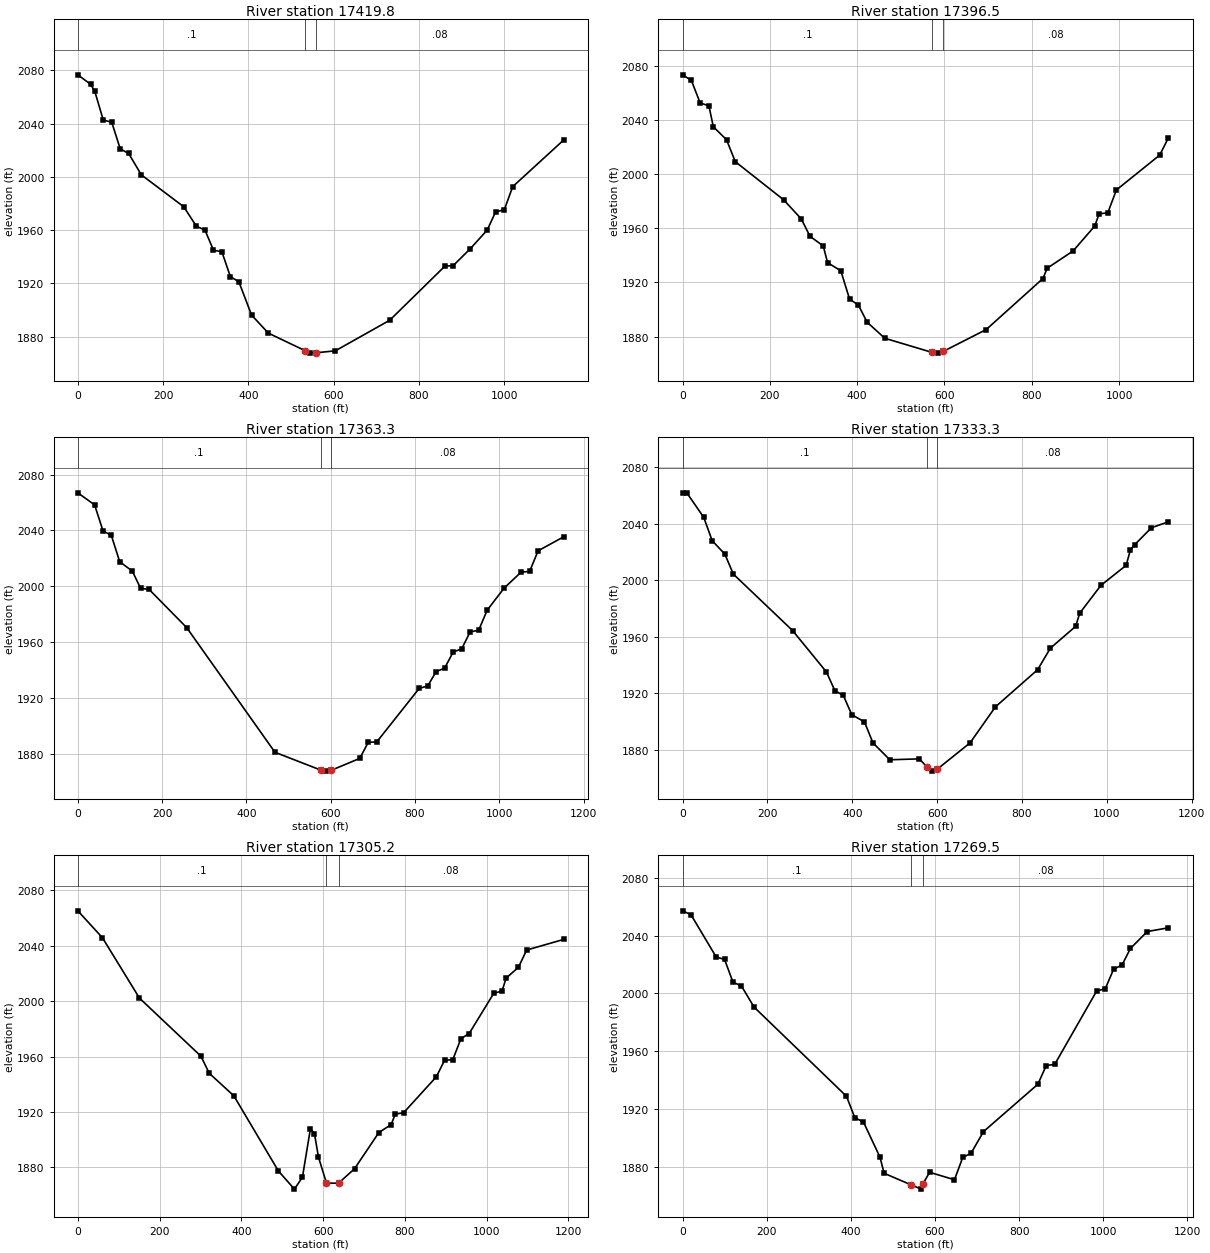
Type RM Length L Ch R = 1 ,17419.8 ,22.5,23.3,24
XS GIS Cut Line= 4
     1800797.646       90976.949     1801054.569       91305.811
     1801254.969       91560.165     1801463.077       91899.304
#Sta/Elev= 30
       0 2076.54    29.8 2069.47    39.7 2064.22    59.6 2042.66    79.5 2040.98
    99.4 2021.01   119.2 2017.52     149 2001.48   248.4 1977.55   278.2 1962.83
   298.1 1960.12     318 1944.97   337.8 1943.77   357.7 1925.12   377.6 1921.31
   407.4 1896.29   446.8 1882.75   532.4 1869.67   544.9 1867.75   557.4 1867.97
   603.8 1869.48   731.3 1892.41   860.5 1932.93   880.4 1933.47   920.2 1946.04
     960 1960.13   979.9 1973.91   999.8 1975.12  1019.7 1992.64    1139 2027.58
#Mann= 3 , 0 , 0
       0      .1       0   532.4    .045       0   557.4     .08       0
Bank Sta=532.4,557.4
XS Rating Curve= 0 ,0
Exp/Cntr=0.3,0.1

Type RM Length L Ch R = 1 ,17396.5 ,33.3,33.2,33.1
XS GIS Cut Line= 4
      1800782.23       90997.503     1801054.569       91334.072
     1801247.262       91593.565     1801434.816       91896.734
#Sta/Elev= 30
       0 2073.59    20.1 2069.52    40.3 2052.83    60.4 2050.62    70.5 2035.15
   100.7 2025.59   120.8 2009.35   231.6 1981.11   271.9 1967.02     292 1954.11
   322.2 1947.01   332.3  1934.6   362.5 1928.65   382.6 1907.65   402.7  1903.3
   422.9 1890.56   463.3 1878.69     572  1868.2   584.5  1867.7     597 1868.94
   695.6 1885.14   825.5 1922.89   835.4 1930.55   894.8 1943.33   944.3 1961.77
   954.2  1970.8     974 1971.45   993.8 1988.42  1092.9 2014.17  1112.7 2026.83
#Mann= 3 , 0 , 0
       0      .1       0     572    .045       0     597     .08       0
Bank Sta=572,597
XS Rating Curve= 0 ,0
Exp/Cntr=0.3,0.1

Type RM Length L Ch R = 1 ,17363.3 ,29.9,30,30.2
XS GIS Cut Line= 4
     1800769.384       91010.349     1801026.308       91352.057
     1801201.015       91585.857     1801434.816       91950.688
#Sta/Elev= 30
       0 2066.89    39.8 2058.27    59.7 2039.69    79.5 2036.42    99.4 2017.54
   129.3 2010.88   149.1 1998.42     169  1997.8   258.5 1970.34   467.8 1881.17
     576 1868.49   588.5 1867.68     601 1868.24   669.1 1876.79   689.2 1888.35
   709.3 1888.55   810.1 1926.91   830.2 1928.63   850.4 1938.92   870.5 1941.44
   890.7 1952.92   910.9 1955.21     931 1967.36   951.2 1968.52   971.3 1982.84
  1011.6 1998.69  1051.9 2010.11  1072.1 2010.63  1092.2 2025.38  1152.7 2035.37
#Mann= 3 , 0 , 0
       0      .1       0     576    .045       0     601     .08       0
Bank Sta=576,601
XS Rating Curve= 0 ,0
Exp/Cntr=0.3,0.1

Type RM Length L Ch R = 1 ,17333.3 ,29.1,28.1,27.1
XS GIS Cut Line= 4
     1800756.538       91036.041     1801005.754       91372.611
     1801260.108       91716.888       1801419.4       91968.673
#Sta/Elev= 30
       0 2061.89      10 2061.89    49.9 2044.56    69.8 2028.04    99.7 2018.51
   119.7 2004.39   259.3 1964.46     339  1935.2     359 1921.94   378.9 1918.56
   398.9 1904.92   428.7 1899.84   448.7 1885.01   488.5 1873.04   558.2 1873.69
   575.5 1868.07     588 1865.01   600.5 1866.45   677.6 1884.99   737.3 1910.45
   836.9 1936.78   866.7 1951.93   926.3 1967.41   936.2 1976.81   985.9 1996.39
  1045.5 2010.62  1055.4 2021.46  1065.3 2025.11  1105.1  2037.2  1144.8 2041.34
#Mann= 3 , 0 , 0
       0      .1       0   575.5    .045       0   600.5     .08       0
Bank Sta=575.5,600.5
XS Rating Curve= 0 ,0
Exp/Cntr=0.3,0.1

Type RM Length L Ch R = 1 ,17305.2 ,36.2,35.7,35.1
XS GIS Cut Line= 4
     1800728.277       91030.903     1800974.923       91385.457
     1801144.492       91601.273     1801396.277        92012.35
#Sta/Elev= 30
       0 2065.18    60.3 2045.73   150.7 2002.23   301.3 1960.26   321.4    1948
   381.7 1931.72   490.7 1877.48   529.9 1864.39   549.5 1872.96   569.1 1908.12
   578.9 1904.45   588.7 1887.54   608.3 1868.73   637.8 1868.66     677 1879.11
   736.5 1905.22   766.6 1910.97   776.7 1918.59   796.8 1919.42   877.1 1945.44
   897.2 1957.33   917.3 1957.79   937.4 1973.01   957.4 1976.65  1017.7 2005.73
  1037.8 2007.25  1047.8 2016.64    1078 2024.44    1098 2036.89  1188.4 2044.53
#Mann= 3 , 0 , 0
       0      .1       0   608.3    .045       0   637.8     .08       0
Bank Sta=608.3,637.8
XS Rating Curve= 0 ,0
Exp/Cntr=0.3,0.1

Type RM Length L Ch R = 1 ,17269.5 ,26.7,29.3,32
XS GIS Cut Line= 4
     1800712.861       91059.164     1800964.646       91431.703
     1801157.338       91668.073     1801365.446       92009.781
#Sta/Elev= 30
       0 2057.13      20 2054.44    79.9  2025.2    99.9 2023.45   119.9 2007.73
   139.9 2005.14   169.9 1990.53   389.7 1928.76   409.7 1913.78   429.7 1911.15
   469.3 1886.64   479.2 1875.47  542.65 1867.53   567.7  1864.5  570.74 1867.85
   587.4 1876.15   646.4    1871   666.1 1886.49   685.7 1889.27   715.3  1904.3
   844.6 1937.09   864.6 1950.07   884.6 1950.81   984.7 2001.77  1004.7 2003.09
  1024.7  2016.7  1044.7 2019.66  1064.7 2031.09  1104.7 2042.81  1154.7 2045.36
#Mann= 3 , 0 , 0
       0      .1       0  542.65    .045       0  570.74     .08       0
Bank Sta=542.65,570.74
XS Rating Curve= 0 ,0
Exp/Cntr=0.3,0.1

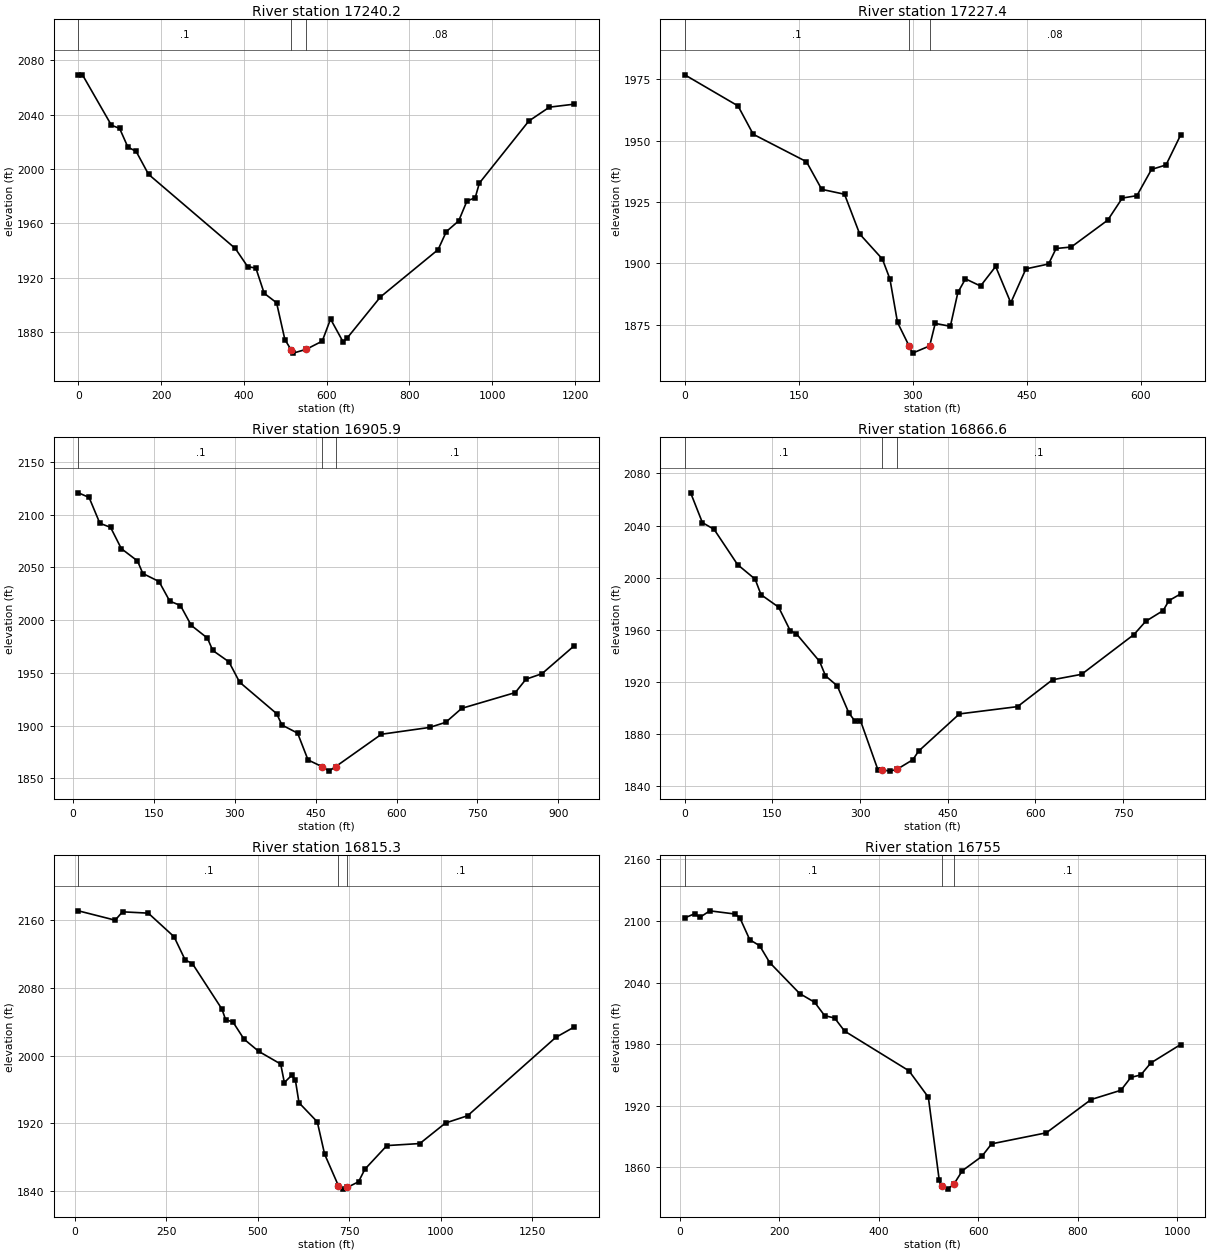
Type RM Length L Ch R = 1 ,17240.2 ,13,12.8,12.6
XS GIS Cut Line= 4
     1800684.599       91059.164       1800951.8       91444.549
     1801098.246       91660.365       1801352.6       92053.458
#Sta/Elev= 30
       0 2069.27      10 2069.27    79.8 2032.22    99.8 2029.78   119.7 2016.07
   139.7  2012.9   169.6 1996.03   379.2 1941.46   409.1 1928.08     429 1926.99
     449 1908.47     479 1901.47     499 1874.43  514.43 1866.67   519.1  1864.4
  550.55  1867.2   589.3 1873.22   609.4  1889.5   639.5 1872.79   649.5 1875.49
   729.8 1905.72   869.2 1940.57   889.2 1953.88     919 1961.74     939 1976.41
   958.9 1978.75   968.9 1989.53  1088.4 2035.24  1138.2 2045.47    1198 2047.67
#Mann= 3 , 0 , 0
       0      .1       0  514.43    .045       0  550.55     .08       0
Bank Sta=514.43,550.55
XS Rating Curve= 0 ,0
Exp/Cntr=0.3,0.1

Type RM Length L Ch R = 1 ,17227.4 ,325.2,321.1,317.4
XS GIS Cut Line= 4
      1800810.73       91257.812     1800938.351       91449.243
     1801096.241       91678.306      1801176.31       91797.951
#Sta/Elev= 30
       0 1976.74      70 1964.09      90 1952.56     160  1941.4   180.1 1930.14
   210.1 1928.15   230.1 1911.95   259.9 1901.78   269.8 1893.68   279.8 1875.99
  295.21  1866.3   299.6  1863.5   322.1 1866.44   329.4  1875.6   349.3 1874.41
   359.2 1888.18   369.2 1893.73     389  1890.8   408.9 1898.76   428.8 1883.98
   448.7 1897.78   478.5 1899.77   488.4 1906.08   508.3 1906.67   556.3  1917.6
   575.5  1926.6   594.7 1927.57   613.9 1938.24     633 1940.07   652.2 1952.24
#Mann= 3 , 0 , 0
       0      .1       0  295.21    .045       0   322.1     .08       0
Bank Sta=295.21,322.1
XS Rating Curve= 0 ,0
Exp/Cntr=0.3,0.1

Type RM Length L Ch R = 1 ,16905.9 ,40.6,39.3,37.9
XS GIS Cut Line= 4
     1800424.571       91326.734     1800633.016       91594.132
     1800776.189       91752.044     1801028.849       92032.075
#Sta/Elev= 30
      10  2120.8    29.9 2116.46    49.9 2091.93    69.8 2088.03    89.7 2067.86
   119.7 2056.19   129.6 2044.27   159.6 2036.67   179.5 2018.09   199.4 2013.88
   219.4 1995.06   249.3 1983.01   259.3 1971.26   289.2  1960.5   309.1 1941.17
   377.8 1911.28   387.5 1900.55   416.6 1892.83   435.9 1867.44   462.2 1860.96
   474.7  1856.8   487.2 1861.07     572 1891.78   661.4 1898.25   691.2 1903.08
   720.9 1916.35   820.2  1931.3     840 1943.97   869.8 1949.24   929.4 1975.66
#Mann= 3 , 0 , 0
      10      .1       0   462.2    .045       0   487.2      .1       0
Bank Sta=462.2,487.2
XS Rating Curve= 0 ,0
Exp/Cntr=0.3,0.1

Type RM Length L Ch R = 1 ,16866.6 ,53.5,51.3,49.1
XS GIS Cut Line= 4
     1800437.204       91476.224     1800628.805       91653.086
     1800875.148       91899.429     1801028.849       92082.607
#Sta/Elev= 30
      10 2065.12    30.1 2042.22    50.1 2037.06    90.3 2009.94   120.3 1998.78
   130.4 1986.83   160.5 1977.24   180.5 1959.07   190.5 1956.99   230.7  1935.5
   240.7 1924.48   260.8 1916.77   280.7 1895.89   290.6    1890   300.6 1889.99
   330.4 1852.24   337.8 1852.24   350.3 1851.21   362.8 1852.53   390.1 1859.95
   400.1 1866.63   469.8 1895.18   569.3 1900.79   629.1 1921.43   678.9 1925.63
   768.5 1956.21   788.5 1966.34   818.4 1974.61   828.3 1982.26   848.3 1987.42
#Mann= 3 , 0 , 0
       0      .1       0   337.8    .045       0   362.8      .1       0
Bank Sta=337.8,362.8
XS Rating Curve= 0 ,0
Exp/Cntr=0.3,0.1

Type RM Length L Ch R = 1 ,16815.3 ,59.4,60.3,61.2
XS GIS Cut Line= 4
     1800229.422       91170.598     1800466.139        91591.43
     1800823.846       91896.532     1801081.605       92217.416
#Sta/Elev= 30
    10.1 2171.46   110.7 2160.38   130.8 2170.28   201.2 2168.71   271.6 2140.77
   301.8 2113.38   321.9 2108.78   402.4 2055.02   412.4 2042.48   432.5  2039.7
   462.7 2019.41   502.8 2004.93   562.9 1989.89   572.9 1967.96   592.9  1976.5
   602.9 1971.17   612.9 1944.02   662.9 1921.36   682.9 1883.07   720.4 1845.86
   732.9 1841.64   745.4 1843.81  775.58 1850.36   792.9 1865.23     853 1893.25
     943 1895.66  1013.2 1920.02  1073.5  1928.6  1314.4 2021.48  1364.6 2033.72
#Mann= 3 , 0 , 0
    10.1      .1       0   720.4    .045       0   745.4      .1       0
Bank Sta=720.4,745.4
XS Rating Curve= 0 ,0
Exp/Cntr=0.3,0.1

Type RM Length L Ch R = 1 ,16755   ,52.7,53.6,54.5
XS GIS Cut Line= 4
      1800254.31       91427.275      1800544.76       91732.565
     1800688.925       91864.009     1800962.414       92141.739
#Sta/Elev= 30
      10 2103.06    30.1 2107.09    40.1 2103.46    60.2 2109.89   110.4 2106.81
   120.4 2103.31   140.5 2081.78   160.5 2075.87   180.6 2059.51   240.8 2029.36
   270.9 2020.86     291 2007.82     311 2005.54   331.1  1992.8   460.4 1954.15
   499.4  1928.4  521.29 1847.57   525.9  1841.5   538.4 1838.94   550.9 1843.95
   567.7 1856.87   606.7 1870.73   626.5 1883.03   736.4 1893.76   826.4 1926.16
   886.3 1935.19   906.3 1947.76   926.3 1950.09   946.3 1961.74  1006.3 1979.72
#Mann= 3 , 0 , 0
      10      .1       0   525.9    .045       0   550.9      .1       0
Bank Sta=525.9,550.9
XS Rating Curve= 0 ,0
Exp/Cntr=0.3,0.1