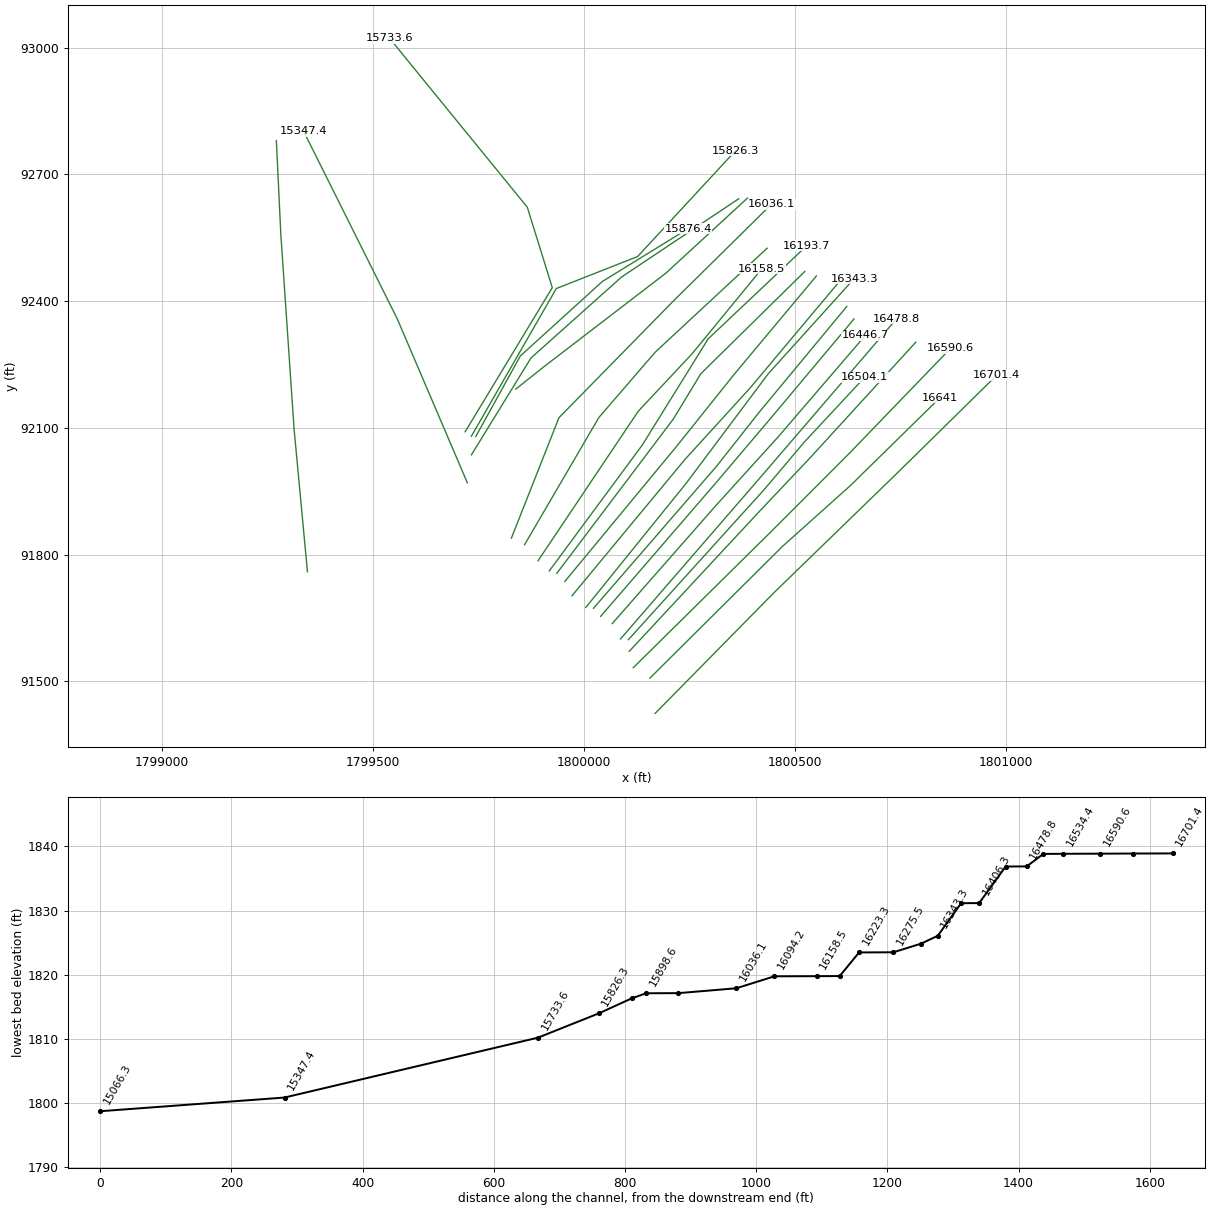
HEC-RAS study Cucumber Creek.prj: Cucumber Creek

--- Cucumber Creek.g01 (geometry) --- (continued)

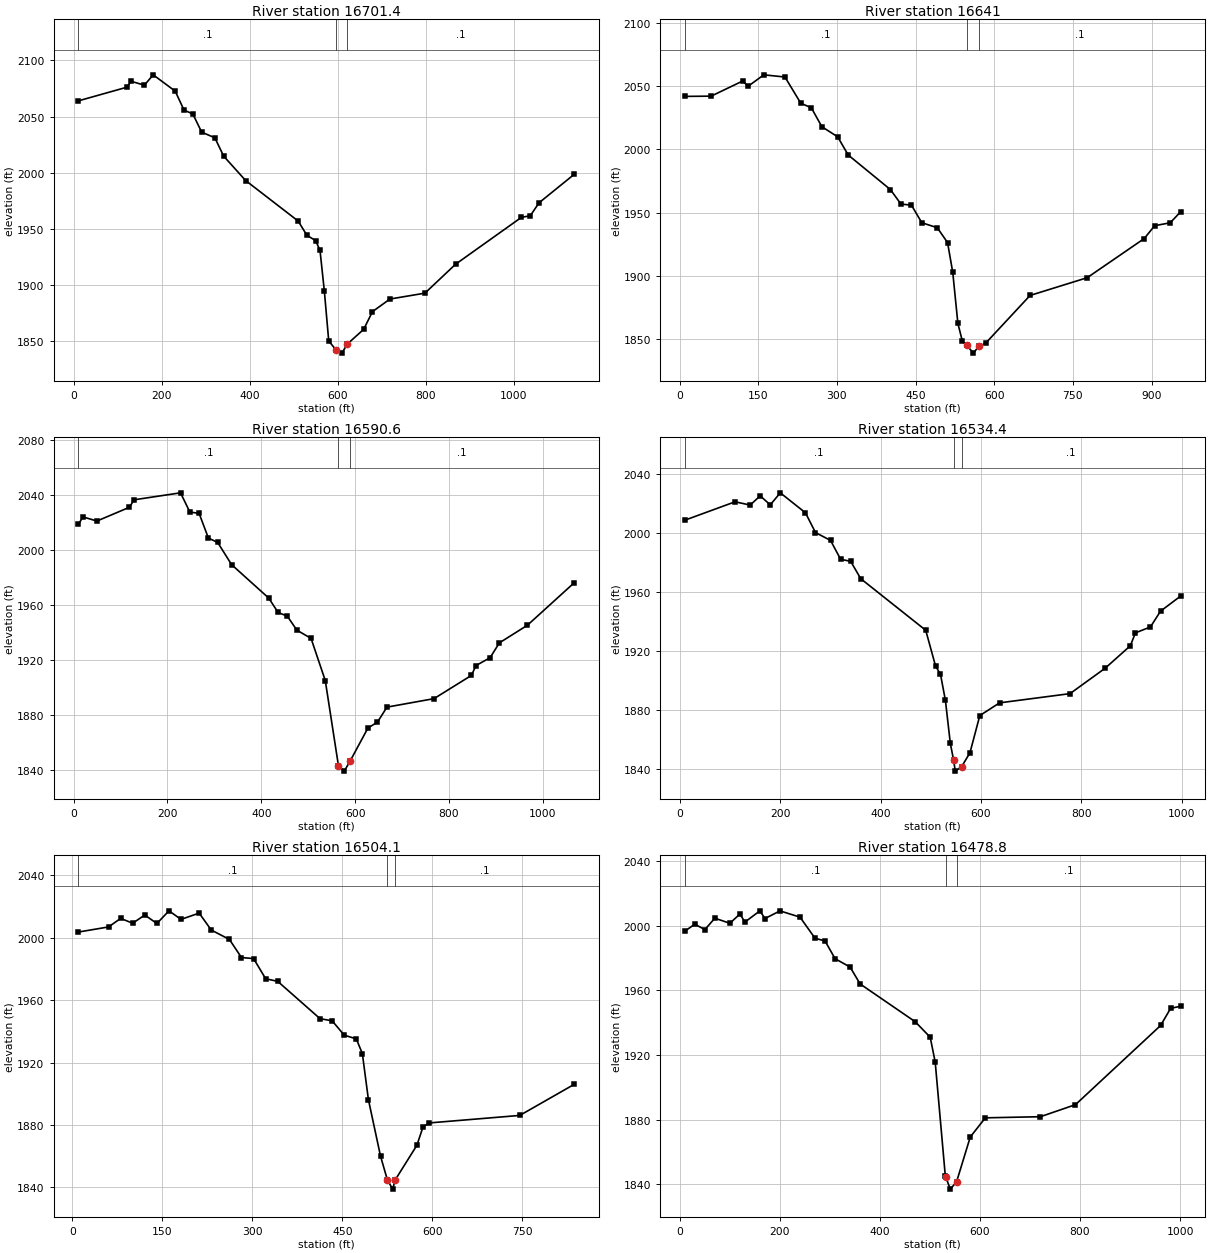
Type RM Length L Ch R = 1 ,16701.4 ,61.5,60.4,59.3
XS GIS Cut Line= 4
     1800169.301       91424.471     1800450.319       91709.812
      1800735.66       91986.506     1800977.768       92224.291
#Sta/Elev= 30
      10 2063.96   120.1 2076.12   130.2 2081.39   160.2 2077.96   180.2 2087.19
   230.3 2072.61   250.3 2055.71   270.3 2052.29   290.4 2036.07   320.4    2031
   340.4 2014.67   390.5 1992.85   509.8 1956.74   529.7 1944.01   549.5 1939.31
   559.5  1930.5   569.4 1894.02   579.3 1849.76   596.7  1841.4   609.2 1838.92
   621.7 1847.08   658.8 1860.16   678.7 1875.93   718.5 1887.18     798 1892.42
   867.8 1918.26  1017.5 1960.07  1037.5 1961.44  1057.5 1973.04  1137.3 1998.38
#Mann= 3 , 0 , 0
      10      .1       0   596.7    .045       0   621.7      .1       0
Bank Sta=596.7,621.7
XS Rating Curve= 0 ,0
Exp/Cntr=0.3,0.1

Type RM Length L Ch R = 1 ,16641   ,48.9,50.5,52
XS GIS Cut Line= 4
     1800156.787       91507.837     1800470.557       91819.488
     1800631.683       91963.653      1800843.69        92171.42
#Sta/Elev= 30
    10.1 2041.91    60.3  2042.1   120.6  2054.1   130.7  2049.9   160.8 2058.96
     201 2057.23   231.2  2036.5   251.3 2032.91   271.4 2017.92   301.5 2009.95
   321.6 1995.57     402 1968.25   422.1  1956.8   442.2 1955.87   461.9 1942.02
   491.4 1938.05     511 1926.31   520.9 1902.79   530.7 1862.34  539.33 1848.22
   547.7 1845.09   560.2  1838.9  570.31 1844.17  583.46 1846.69   668.3 1884.51
   777.2 1898.54     886 1929.51   905.8 1939.66   935.5 1941.97   955.3 1950.65
#Mann= 3 , 0 , 0
    10.1      .1       0   547.7    .045       0  570.31      .1       0
Bank Sta=547.7,570.31
XS Rating Curve= 0 ,0
Exp/Cntr=0.3,0.1

Type RM Length L Ch R = 1 ,16590.6 ,55.4,56.1,56.9
XS GIS Cut Line= 4
     1800117.421       91532.554     1800441.672       91852.483
     1800627.576       92038.387     1800869.684       92289.141
#Sta/Elev= 30
     9.9 2018.61    19.8 2024.07    49.5 2021.06   118.8 2031.08   128.7 2036.53
   227.8 2041.61   247.6 2027.63   267.4 2026.63   287.2 2008.65     307 2005.47
   336.7 1989.28   415.9 1964.92   435.7 1954.49   455.5 1951.75   475.7 1941.61
   506.1 1935.55   536.4 1904.83   564.4 1842.97   576.9 1838.88   589.4 1846.25
   627.4 1870.31   647.6 1874.54   667.9  1885.5   768.2 1891.68   847.9  1908.6
   857.8 1915.81   887.7 1921.48   907.6 1932.32   967.4 1945.17    1067 1976.07
#Mann= 3 , 0 , 0
     9.9      .1       0   564.4    .045       0   589.4      .1       0
Bank Sta=564.4,589.4
XS Rating Curve= 0 ,0
Exp/Cntr=0.3,0.1

Type RM Length L Ch R = 1 ,16534.4 ,28.7,30.3,31.9
XS GIS Cut Line= 4
     1800108.025       91571.439     1800421.796       91908.531
      1800536.28       92029.375     1800786.448       92302.864
#Sta/Elev= 30
      10 2008.89   110.1 2021.36   140.2 2019.15   160.2  2025.4   180.2 2019.29
   200.2 2027.44   250.3 2013.92   270.3 2000.53   300.3 1995.18   320.4 1982.39
   340.4 1981.04   360.4 1969.27   489.9  1934.3   509.5 1910.04   519.3 1904.48
   529.1 1886.77   538.9 1857.64  545.45 1846.27   548.7 1838.86   561.2 1841.76
     578 1851.32   597.6 1876.51     637 1885.13   777.3 1891.37   847.4 1908.62
   897.5 1923.83   907.5 1932.53   937.5 1936.57   957.6 1947.26   997.6 1957.48
#Mann= 3 , 0 , 0
      10      .1       0  545.45    .045       0   561.2      .1       0
Bank Sta=545.45,561.2
XS Rating Curve= 0 ,0
Exp/Cntr=0.3,0.1

Type RM Length L Ch R = 1 ,16504.1 ,25.6,25.3,25
XS GIS Cut Line= 4
     1800105.905          91599.     1800430.276       91957.292
     1800521.439       92065.416     1800665.604       92220.181
#Sta/Elev= 30
    10.1 2003.71    60.4 2006.98    80.6 2012.44   100.7 2009.38   120.8 2014.62
     141  2009.2   161.1 2017.32   181.2 2011.83   211.4 2015.86   231.6    2005
   261.8 1998.98   281.9 1987.37   302.1 1986.69   322.2 1973.77   342.3 1972.09
   412.8 1948.16     433 1946.79   453.1 1937.58   473.2 1935.21   483.3  1925.8
   493.4 1896.24   513.6 1859.98  524.91 1844.89   533.8 1838.84  538.07 1844.77
   574.2 1866.97   584.3 1878.63   594.4 1881.28   745.6 1886.11   836.2 1906.02
#Mann= 3 , 0 , 0
    10.1      .1       0  524.91    .045       0  538.07      .1       0
Bank Sta=524.91,538.07
XS Rating Curve= 0 ,0
Exp/Cntr=0.3,0.1

Type RM Length L Ch R = 1 ,16478.8 ,32.9,32.1,31.4
XS GIS Cut Line= 3
     1800087.155       91600.605     1800414.963       91978.985
     1800741.279        92358.58
#Sta/Elev= 30
      10 1996.57      30 2000.93    50.1 1997.58    70.1 2004.63   100.1 2001.49
   120.2 2007.23   130.2 2002.24   160.2  2009.2   170.2 2004.41   200.3 2009.16
   240.3  2005.3   270.3 1992.24   290.4 1990.52   310.4 1979.57   340.4 1974.39
   360.5 1963.92   470.6 1940.54   500.6 1930.93   510.6 1915.49   530.7 1845.31
  531.95 1844.18   540.7 1836.89   553.2 1841.33   580.7 1869.19   610.8 1881.03
   720.9 1881.73     791 1889.19   961.2 1938.21   981.2 1948.81  1001.2 1950.14
#Mann= 3 , 0 , 0
      10      .1       0  531.95    .045       0   553.2      .1       0
Bank Sta=531.95,553.2
XS Rating Curve= 0 ,0
Exp/Cntr=0.3,0.1

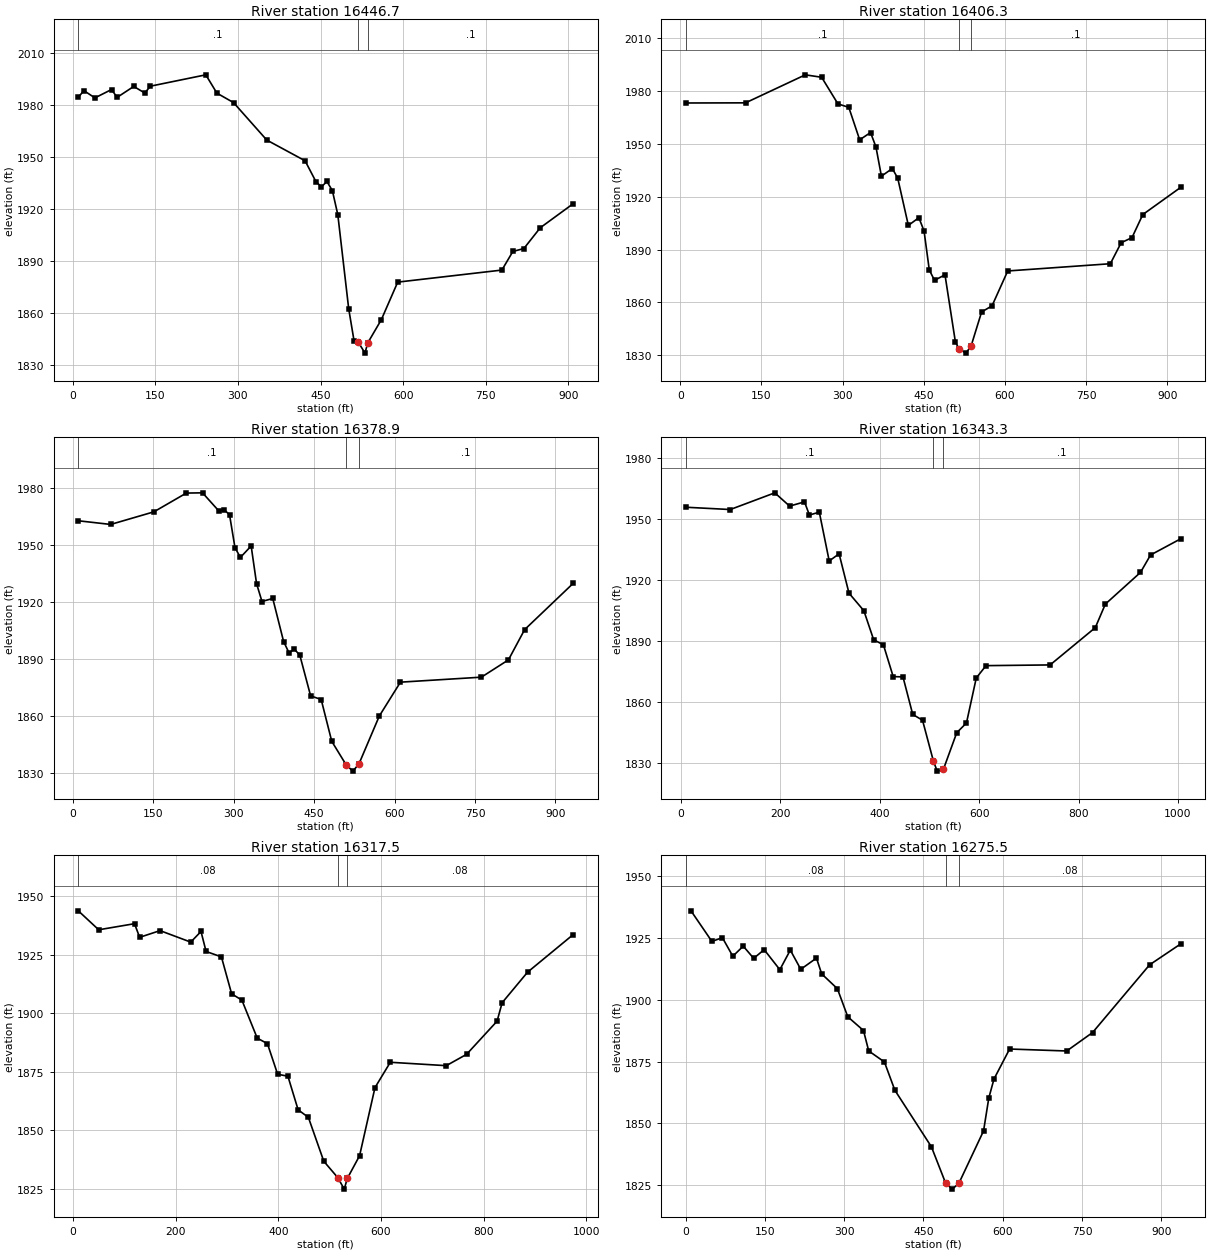
Type RM Length L Ch R = 1 ,16446.7 ,39.5,40.4,41.2
XS GIS Cut Line= 4
     1800067.744       91637.162     1800313.672       91917.011
     1800459.957       92078.136     1800667.724       92319.825
#Sta/Elev= 30
    10.1 1984.55    20.1 1988.51    40.3 1984.29    70.5 1989.11    80.6 1984.57
   110.8 1990.89   130.9  1987.1     141 1991.04   241.7  1997.6   261.8 1987.03
     292 1981.57   352.4 1959.93     422 1947.95   441.8 1935.85   451.7 1932.91
   461.6 1936.01   471.5 1930.76   481.4 1916.86   501.2 1862.48     511 1843.79
   518.3 1843.36   530.8 1836.87  535.67 1842.69   560.5 1856.21   590.2 1877.88
   779.4 1884.84   799.3 1895.58   819.3 1897.27   849.1 1909.28   908.9 1923.17
#Mann= 3 , 0 , 0
    10.1      .1       0   518.3    .045       0  535.67      .1       0
Bank Sta=518.3,535.67
XS Rating Curve= 0 ,0
Exp/Cntr=0.3,0.1

Type RM Length L Ch R = 1 ,16406.3 ,26.5,27.5,28.5
XS GIS Cut Line= 4
     1800040.183       91654.122     1800309.432       91965.773
     1800440.876       92120.538     1800640.163       92357.986
#Sta/Elev= 30
      10 1973.27   120.5 1973.35     231 1989.27   261.2 1987.88   291.3 1972.77
   311.4 1970.79   331.5 1952.35   351.6 1956.48   361.6 1948.29   371.7 1931.69
   391.8 1936.04   401.8 1930.61   421.5 1903.72   440.9 1908.11   450.5  1900.6
   460.2 1878.41   469.9 1872.51   489.2 1875.66   508.5 1837.39   515.4 1833.53
   527.9 1831.16   537.5 1835.25   556.9 1854.54   576.2 1858.04   605.2 1877.84
   794.9 1881.95   814.9 1893.89   834.9 1896.77   854.9 1909.89   924.9 1925.32
#Mann= 3 , 0 , 0
      10      .1       0   515.4    .045       0   537.5      .1       0
Bank Sta=515.4,537.5
XS Rating Curve= 0 ,0
Exp/Cntr=0.3,0.1

Type RM Length L Ch R = 1 ,16378.9 ,34.9,35.6,36.3
XS GIS Cut Line= 4
     1800023.222       91673.203     1800313.672       92008.174
     1800417.556       92139.619     1800623.203       92387.667
#Sta/Elev= 30
    10.1 1962.84    70.5 1960.91   151.1 1967.54   211.6 1977.41   241.8 1977.54
   272.1 1968.05   282.1 1968.66   292.2 1965.99   302.3 1948.72   312.4 1943.55
   332.5 1949.58   342.6 1929.75   352.7 1920.37   372.8 1921.97     393 1899.33
   403.1 1893.36   413.1 1895.26   423.2  1892.2   443.4 1870.73   463.1 1868.81
   482.8 1846.82   509.7 1834.42   522.2 1831.14  533.55 1834.94   571.5 1860.13
   610.9 1877.94   761.9 1880.57   812.3 1889.66   842.5 1905.57   933.1 1929.93
#Mann= 3 , 0 , 0
    10.1      .1       0   509.7    .045       0  533.55      .1       0
Bank Sta=509.7,533.55
XS Rating Curve= 0 ,0
Exp/Cntr=0.3,0.1

Type RM Length L Ch R = 1 ,16343.3 ,28.5,25.8,23.1
XS GIS Cut Line= 4
     1800005.013       91675.225     1800242.798       91969.213
     1800437.349       92228.614     1800640.546       92453.429
#Sta/Elev= 30
      10 1955.59    99.5 1954.46   189.1 1962.66   218.9 1956.14   248.8 1958.22
   258.7 1951.76   278.6 1953.18   298.5 1929.22   318.4 1932.72   338.3 1913.41
   368.2  1904.8   387.9 1890.55   407.6 1888.02   427.2 1872.45   446.9 1872.31
   466.5 1853.88   486.2 1851.04  508.09 1830.97   515.7 1826.05   528.2 1826.93
     555 1844.89   574.6 1849.71   594.3 1871.79   613.9 1877.83   742.8 1878.18
   833.7 1896.49   853.9 1908.04   924.6  1923.6   944.8 1932.14  1005.4 1940.08
#Mann= 3 , 0 , 0
      10      .1       0  508.09    .045       0   528.2      .1       0
Bank Sta=508.09,528.2
XS Rating Curve= 0 ,0
Exp/Cntr=0.3,0.1

Type RM Length L Ch R = 1 ,16317.5 ,40.2,42,43.8
XS GIS Cut Line= 4
     1799972.341       91702.884      1800239.47       92025.135
     1800394.235        92194.74     1800604.122       92444.909
#Sta/Elev= 30
      10 1943.74    49.8 1935.64   119.6 1938.24   129.6 1932.42   169.4 1935.28
   229.2 1930.37   249.2 1934.91   259.1 1926.37     289 1924.06   308.9 1908.27
   328.9 1905.58   358.8 1889.34   378.7 1886.97   398.6  1873.9   418.6 1873.07
   438.5 1858.71   458.5 1855.48   488.5 1836.74   515.9  1829.7   528.4 1824.81
  534.35 1829.36   558.3 1839.08   588.3 1868.18   618.2 1879.02   727.3 1877.57
   766.9 1882.42   826.3 1896.58   836.2 1904.47   885.7 1917.51   974.7 1933.59
#Mann= 3 , 0 , 0
      10     .08       0   515.9    .045       0  534.35     .08       0
Bank Sta=515.9,534.35
XS Rating Curve= 0 ,0
Exp/Cntr=0.3,0.1

Type RM Length L Ch R = 1 ,16275.5 ,48.6,52.1,55.7
XS GIS Cut Line= 4
      1799955.38       91736.805     1800220.389       92056.936
     1800356.074       92226.542      1800551.12       92459.749
#Sta/Elev= 30
     9.9 1935.95    49.5 1923.58    69.3 1925.11    89.1  1917.6   108.8 1921.68
   128.6 1916.74   148.4 1920.26   178.1 1912.16   197.9 1920.08   217.7 1912.32
   247.4 1916.85   257.3 1910.46     287 1904.48   306.7 1893.12   336.4 1887.58
   346.3 1879.32     376 1874.87   395.8 1863.44     465 1840.57   491.9 1825.89
   504.4 1823.47   516.9 1825.78   563.7 1847.01   573.6 1860.28   583.4 1867.96
     613  1880.1   721.1  1879.3   770.1 1886.77     878 1914.13   936.8 1922.57
#Mann= 3 , 0 , 0
       0     .08       0   491.9    .045       0   516.9     .08       0
Bank Sta=491.9,516.9
XS Rating Curve= 0 ,0
Exp/Cntr=0.3,0.1

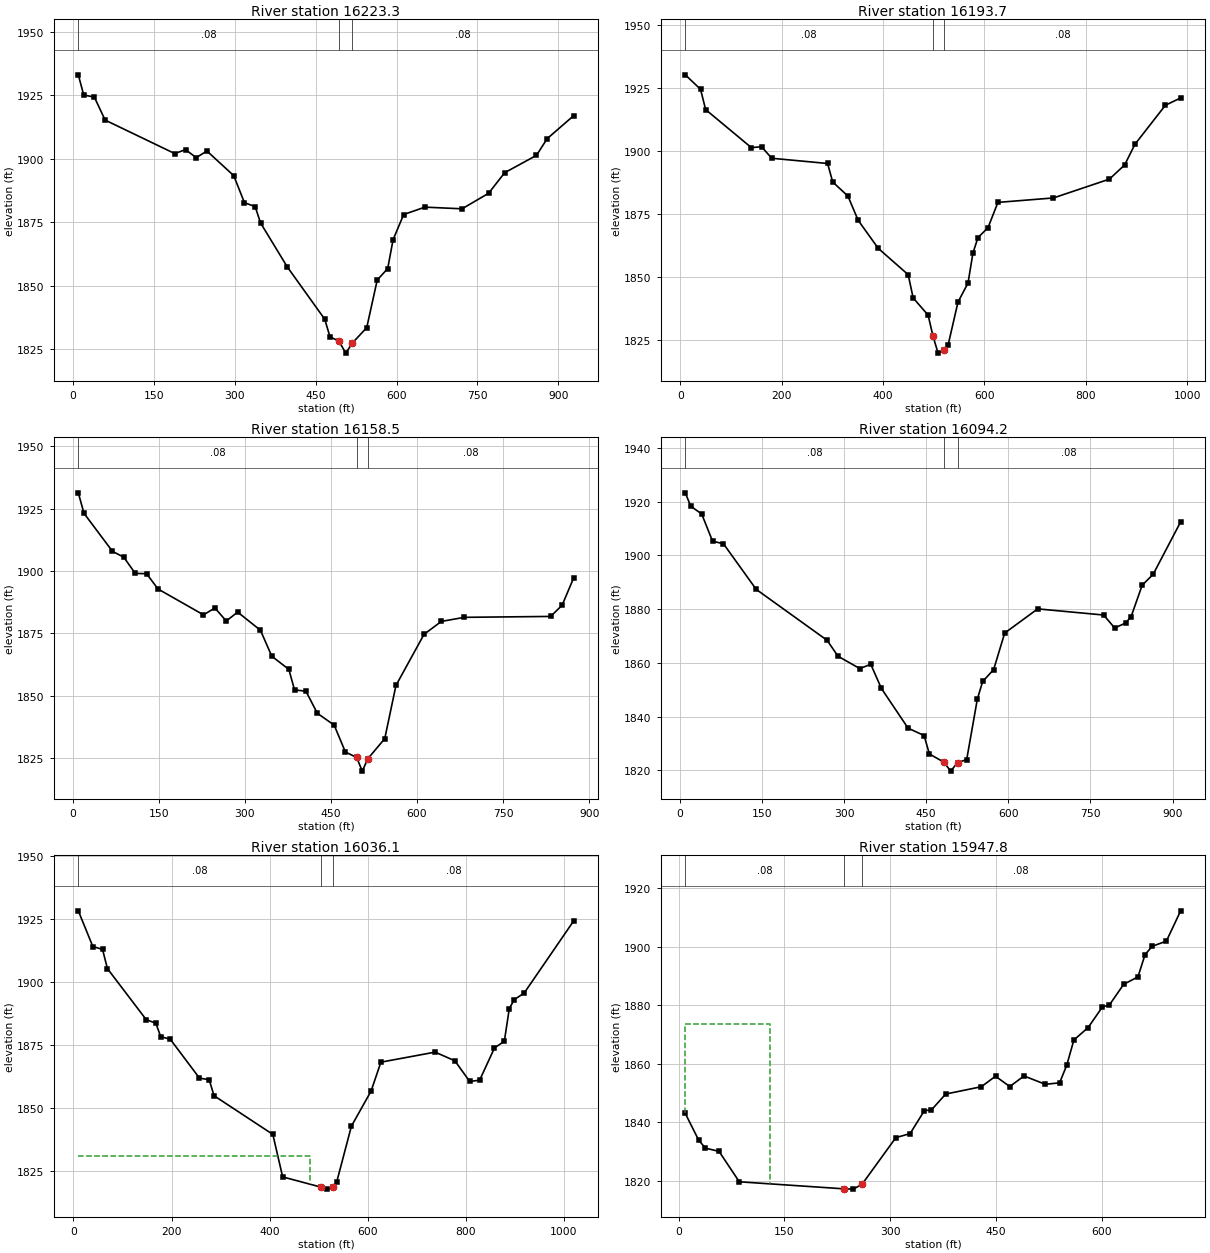
Type RM Length L Ch R = 1 ,16223.3 ,29.9,29.6,29.4
XS GIS Cut Line= 4
     1799936.299       91755.886     1800211.909       92120.538
     1800277.631       92228.662     1800523.559        92470.35
#Sta/Elev= 30
     9.9  1933.1    19.9 1925.17    39.7 1924.31    59.6 1915.27   188.8 1902.07
   208.7 1903.64   228.5 1900.47   248.4 1903.08   298.1 1893.38     318 1882.71
   337.8  1881.2   347.8 1874.75   397.5 1857.39   466.8 1836.82   476.6 1829.87
   493.3 1828.15   505.8 1823.45   518.3 1827.49   544.7 1833.48   564.2 1852.28
   583.6 1856.76   593.5 1868.08   613.2 1878.06   652.6 1880.97   721.5 1880.31
   770.8 1886.45   800.4 1894.52   859.5 1901.38   879.2 1907.93   928.4    1917
#Mann= 3 , 0 , 0
     9.9     .08       0   493.3    .045       0   518.3     .08       0
Bank Sta=493.3,518.3
XS Rating Curve= 0 ,0
Exp/Cntr=0.3,0.1

Type RM Length L Ch R = 1 ,16193.7 ,40.7,35.2,29.8
XS GIS Cut Line= 4
     1799918.547       91761.692     1800139.038       92060.003
     1800294.678       92310.758     1800528.139       92531.249
#Sta/Elev= 30
      10  1930.1    40.1 1924.35    50.1 1916.32   140.4 1901.23   160.4 1901.59
   180.5 1897.02   290.7 1894.95   300.8  1887.6   330.8 1882.03   350.9 1872.45
   390.6 1861.31   449.7 1850.86   459.5 1841.64     489 1834.83   498.8 1826.37
   508.7 1819.76   521.2 1820.98   528.4 1822.92     548 1840.03   567.7 1847.53
   577.5  1859.5   587.4 1865.59   607.1 1869.46   626.7 1879.52   736.3 1881.29
   846.7 1888.75   876.8 1894.39   896.9 1902.52   957.1 1918.04   987.2 1920.93
#Mann= 3 , 0 , 0
      10     .08       0   498.8    .045       0   521.2     .08       0
Bank Sta=498.8,521.2
XS Rating Curve= 0 ,0
Exp/Cntr=0.3,0.1

Type RM Length L Ch R = 1 ,16158.5 ,63.1,64.3,65.4
XS GIS Cut Line= 4
     1799891.778       91785.567     1800129.226       92139.619
      1800256.43       92275.303     1800421.796        92476.71
#Sta/Elev= 30
     9.9 1931.39    19.8 1923.17    69.4 1907.92    89.2 1905.54   109.1 1899.07
   128.9 1898.94   148.7 1892.82     228 1882.44   247.9  1885.2   267.7 1879.96
   287.5 1883.54   327.2 1876.26     347 1865.84   376.7 1860.55   386.6 1852.34
   406.5 1851.79   426.3 1842.96   455.7 1838.18   475.2 1827.42   494.8 1825.23
   504.6 1819.74   514.4 1824.73   543.8 1832.78   563.3  1854.1   612.3 1874.64
   642.4  1879.8   682.5 1881.44   832.8  1881.8   852.8 1886.29   872.9 1897.25
#Mann= 3 , 0 , 0
     9.9     .08       0   494.8    .045       0   514.4     .08       0
Bank Sta=494.8,514.4
XS Rating Curve= 0 ,0
Exp/Cntr=0.3,0.1

Type RM Length L Ch R = 1 ,16094.2 ,59.9,58.1,56.3
XS GIS Cut Line= 4
     1799859.977       91823.728     1800035.943       92124.778
     1800169.507       92279.543     1800434.516       92525.472
#Sta/Elev= 30
      10 1923.32    19.9 1918.34    39.9 1915.46    59.8 1905.31    79.7 1904.36
   139.5 1887.38     269 1868.42   288.9 1862.49   328.8 1857.89   348.7 1859.51
   368.2 1850.48   416.8 1835.73   446.1 1832.97   455.8 1826.11   482.2 1823.06
   494.7 1819.72   507.2 1822.92   523.9 1823.98   543.4 1846.55   553.1 1853.09
   573.2 1857.54   593.3 1871.11   653.6 1880.12   774.1 1877.83   794.2    1873
   814.2 1874.86   824.3 1877.27   844.4 1888.92   864.5 1892.99   914.7 1912.52
#Mann= 3 , 0 , 0
      10     .08       0   482.2    .045       0   507.2     .08       0
Bank Sta=482.2,507.2
XS Rating Curve= 0 ,0
Exp/Cntr=0.3,0.1

Type RM Length L Ch R = 1 ,16036.1 ,92.2,88.4,84.5
XS GIS Cut Line= 4
     1799828.855       91839.404     1799941.402       92124.294
     1800214.943       92403.095      1800444.94        92629.76
#Sta/Elev= 30
     9.9 1928.11    39.5 1913.97    59.3 1912.84    69.2 1905.23   148.2 1885.04
     168 1883.55   177.9 1878.28   197.6 1877.19   256.9 1861.83   276.7 1861.21
   286.6 1854.87   406.5 1839.53   426.5  1822.7   504.1 1818.67   516.6 1817.85
   529.1 1818.65   536.7 1820.66   566.7  1842.8   606.8  1856.7   626.8 1868.15
   737.3 1872.13   777.6 1868.69   807.9 1860.51   828.1    1861   858.4 1873.79
   878.5 1876.46   888.6  1889.4   898.7 1892.92   918.9 1895.53  1019.8  1924.1
#Mann= 3 , 0 , 0
     9.9     .08       0   504.1    .045       0   529.1     .08       0
#XS Ineff= 2 , 0
          482.56 1831.02
Permanent Ineff=
       F       F
Bank Sta=504.1,529.1
XS Rating Curve= 0 ,0
Exp/Cntr=0.3,0.1

Type RM Length L Ch R = 1 ,15947.8 ,47,49.2,51.4
XS GIS Cut Line= 4
     1799839.243       92192.093     1799906.618       92245.622
     1800194.776       92466.542     1800387.824       92644.057
#Sta/Elev= 30
     9.6 1842.98    28.7 1833.78    38.2 1831.11    57.4 1830.01    86.1  1819.6
   234.9 1817.18   247.4 1817.09   259.9 1818.71   307.9 1834.71   328.1 1836.09
   348.3 1843.94   358.4 1844.21   378.5 1849.62     429 1852.13   449.1 1855.72
   469.3 1852.19   489.5 1855.81   519.8 1852.95   539.9 1853.47     550 1859.47
   560.1 1868.11   580.3 1872.38   600.5 1879.41   610.5 1880.12   630.7 1887.18
   650.9 1889.71     661 1897.36   671.1 1900.18   691.2 1901.96   711.4 1912.32
#Mann= 3 , 0 , 0
     9.6     .08       0   234.9    .045       0   259.9     .08       0
#XS Ineff= 2 , 0
          129.43 1873.51
Permanent Ineff=
       F       F
Bank Sta=234.9,259.9
XS Rating Curve= 0 ,0
Exp/Cntr=0.3,0.1

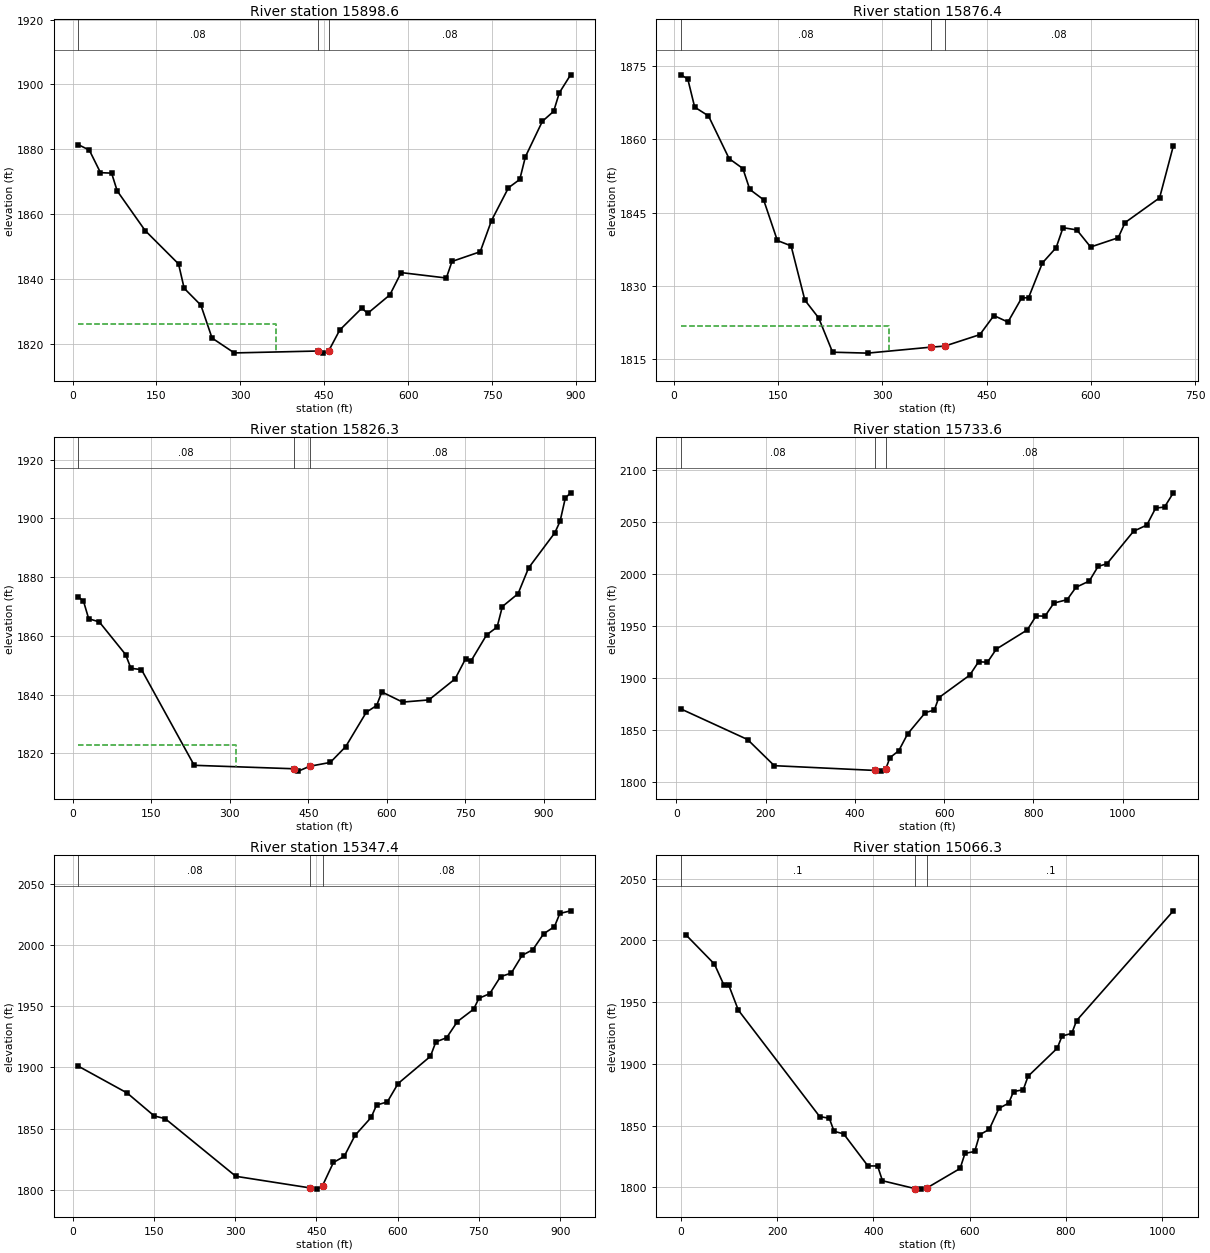
Type RM Length L Ch R = 1 ,15898.6 ,22.1,22.1,22.2
XS GIS Cut Line= 4
     1799733.968       92036.286     1799875.112       92265.643
     1800089.797       92457.385     1800367.107       92642.439
#Sta/Elev= 30
      10 1881.44    29.9 1879.75    49.9 1872.78    69.8 1872.63    79.8 1867.14
   129.7 1854.92   189.5  1844.6   199.5 1837.09   229.4 1831.88   249.4 1821.72
   289.2 1817.13     438 1817.72  447.88 1817.07   457.9 1817.74   477.7  1824.2
   517.4 1830.98   527.4 1829.31   567.3 1835.05   587.5 1841.93   668.3 1840.26
   678.4 1845.37   728.9 1848.37   749.1 1858.01   779.4 1868.12   799.6 1870.69
   809.7  1877.7     840 1888.63   860.2 1891.72   870.3 1897.42   890.5 1902.98
#Mann= 3 , 0 , 0
      10     .08       0     438    .045       0   457.9     .08       0
#XS Ineff= 2 , 0
          364.15 1826.17
Permanent Ineff=
       F       F
Bank Sta=438,457.9
XS Rating Curve= 0 ,0
Exp/Cntr=0.3,0.1

Type RM Length L Ch R = 1 ,15876.4 ,60.3,50.1,40
XS GIS Cut Line= 4
     1799744.313       92079.645     1799849.912       92270.443
      1800044.31       92446.842     1800247.108        92571.64
#Sta/Elev= 30
     9.9 1873.14    19.8 1872.29    29.7 1866.54    49.6 1864.74    79.3 1856.01
    99.1 1853.99     109 1849.72   128.9 1847.61   148.7 1839.28   168.5 1838.18
   188.3 1827.09   208.2 1823.45   228.2 1816.45   278.6 1816.26   369.5 1817.48
   389.7  1817.7   440.2 1820.04   460.4 1823.94   480.6 1822.61   500.4 1827.54
   510.3 1827.59   530.2 1834.69     550 1837.82   559.9  1841.9   579.8 1841.44
   599.6 1837.95   639.3 1839.84   649.2 1842.94   698.9    1848   718.7 1858.63
#Mann= 3 , 0 , 0
     9.9     .08       0   369.5    .045       0   389.7     .08       0
#XS Ineff= 2 , 0
          308.87 1821.85
Permanent Ineff=
       F       F
Bank Sta=369.5,389.7
XS Rating Curve= 0 ,0
Exp/Cntr=0.3,0.1

Type RM Length L Ch R = 1 ,15826.3 ,49.7,92.7,135.7
XS GIS Cut Line= 4
     1799733.968       92080.502     1799935.111       92430.042
     1800127.696       92505.812     1800359.528       92756.063
#Sta/Elev= 30
    10.1 1873.25    20.2 1871.83    30.2  1865.8    50.4 1864.73   100.8  1853.6
   110.9 1848.92   131.1 1848.48   231.9  1815.9     423 1814.72  431.07 1813.92
   452.6 1815.57     492 1816.88   521.5 1822.26     561 1833.99   580.7 1836.26
   590.5 1840.88   630.3 1837.42   680.5 1838.16   730.6 1845.32   750.7 1852.17
   760.7 1851.32   790.8 1860.28   810.9 1862.96   820.9 1869.93     851 1874.33
   871.1  1883.1   921.3 1895.07   931.3    1899   941.3 1906.89   951.4 1908.66
#Mann= 3 , 0 , 0
    10.1     .08       0     423    .045       0   452.6     .08       0
#XS Ineff= 2 , 0
          311.73 1822.68
Permanent Ineff=
       F       F
Bank Sta=423,452.6
XS Rating Curve= 0 ,0
Exp/Cntr=0.3,0.1

Type RM Length L Ch R = 1 ,15733.6 ,383.2,386.2,390.7
XS GIS Cut Line= 4
      1799719.23       92091.029     1799925.569        92432.12
     1799866.454       92622.467      1799540.31       93022.256
#Sta/Elev= 30
      10 1869.99   159.5 1840.53   219.3 1815.38   445.9 1810.77   458.4 1810.13
  469.44 1812.42   478.4 1823.02   498.3 1829.75   518.2 1845.94   558.1 1866.56
     578 1868.85     588 1880.78   657.5 1902.56   677.3 1915.43   697.2 1914.95
     717  1927.6   786.5 1946.09   806.3  1959.6   826.2 1959.29     846 1971.91
   875.8 1975.18   895.6 1987.09   925.4 1993.13   945.2 2007.22   965.1 2009.79
  1024.6 2041.02  1054.4 2047.02  1074.2 2063.35  1094.1 2064.35  1113.9 2078.05
#Mann= 3 , 0 , 0
      10     .08       0   445.9    .045       0  469.44     .08       0
Bank Sta=445.9,469.44
XS Rating Curve= 0 ,0
Exp/Cntr=0.3,0.1

Type RM Length L Ch R = 1 ,15347.4 ,290.5,281.1,270.1
XS GIS Cut Line= 3
     1799724.424       91970.178     1799558.646       92357.743
     1799336.241       92802.963
#Sta/Elev= 30
      10 1901.13   100.4 1879.19   150.5 1860.45   170.6 1858.28   301.1 1811.24
   438.9 1801.72   451.4 1800.78   461.3 1803.71   481.3 1822.54   501.2 1827.49
   521.1 1844.58   550.9 1859.23   560.9 1869.32   580.8 1871.92   600.7 1886.91
   660.4  1909.1   670.4 1920.83   690.3 1924.28   710.2 1937.45     740 1947.47
     750 1956.44   769.9  1960.2   789.8 1974.07   809.7 1976.98   829.6 1991.41
   849.5 1996.09   869.4 2009.02   889.4 2014.87   899.3  2025.6   919.2 2027.76
#Mann= 3 , 0 , 0
      10     .08       0   438.9    .045       0   461.3     .08       0
Bank Sta=438.9,461.3
XS Rating Curve= 0 ,0
Exp/Cntr=0.3,0.1

Type RM Length L Ch R = 1 ,15066.3 ,380.8,369.1,359
XS GIS Cut Line= 4
     1799345.676       91759.762     1799314.113       92096.427
     1799282.551       92559.342      1799272.03       92780.278
#Sta/Elev= 30
     9.9 2004.65    69.6 1980.82    89.5 1963.67    99.5 1963.67   119.3 1943.53
   288.4 1857.35   308.3 1856.01   318.3 1845.42   338.1  1843.4   388.6 1817.41
   408.7  1817.4   418.8 1805.42     487 1799.01   499.5 1798.64     512 1799.77
   580.2 1815.37   590.3 1827.59   610.5 1829.11   620.6  1842.6   640.7 1847.01
   660.9 1864.03   681.1 1868.24   691.2 1877.61   711.4 1879.08   721.4    1890
     782  1912.7     792 1922.54   812.2 1924.72   822.2 1935.06  1023.3  2023.9
#Mann= 3 , 0 , 0
       0      .1       0     487    .045       0     512      .1       0
Bank Sta=487,512
XS Rating Curve= 0 ,0
Exp/Cntr=0.3,0.1