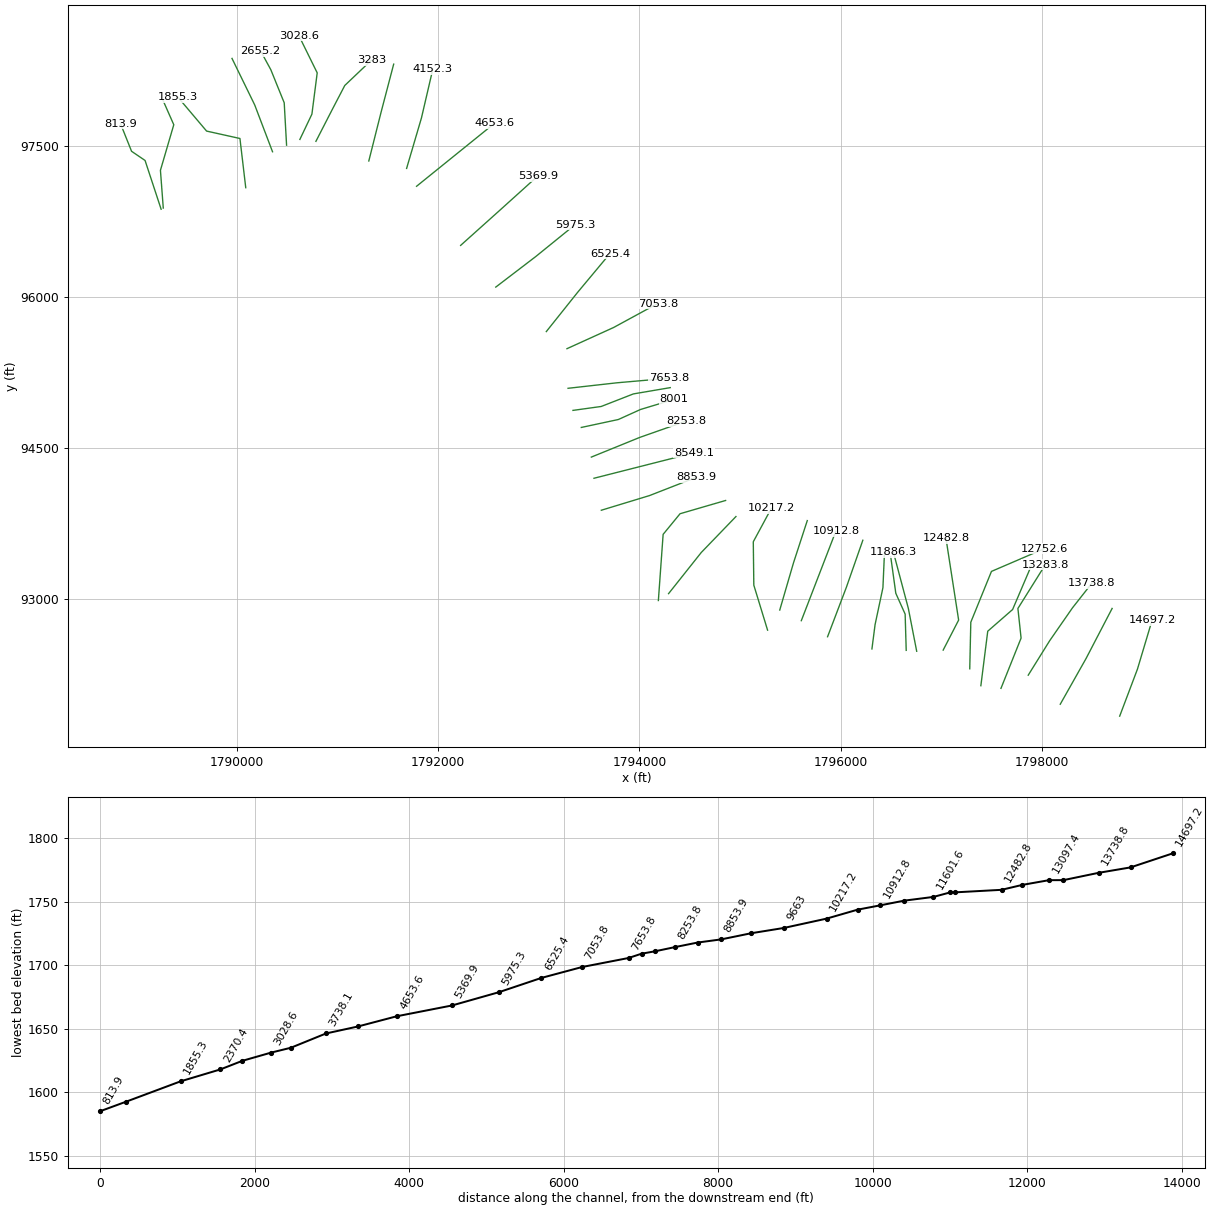
HEC-RAS study Cucumber Creek.prj: Cucumber Creek

--- Cucumber Creek.g01 (geometry) --- (continued)

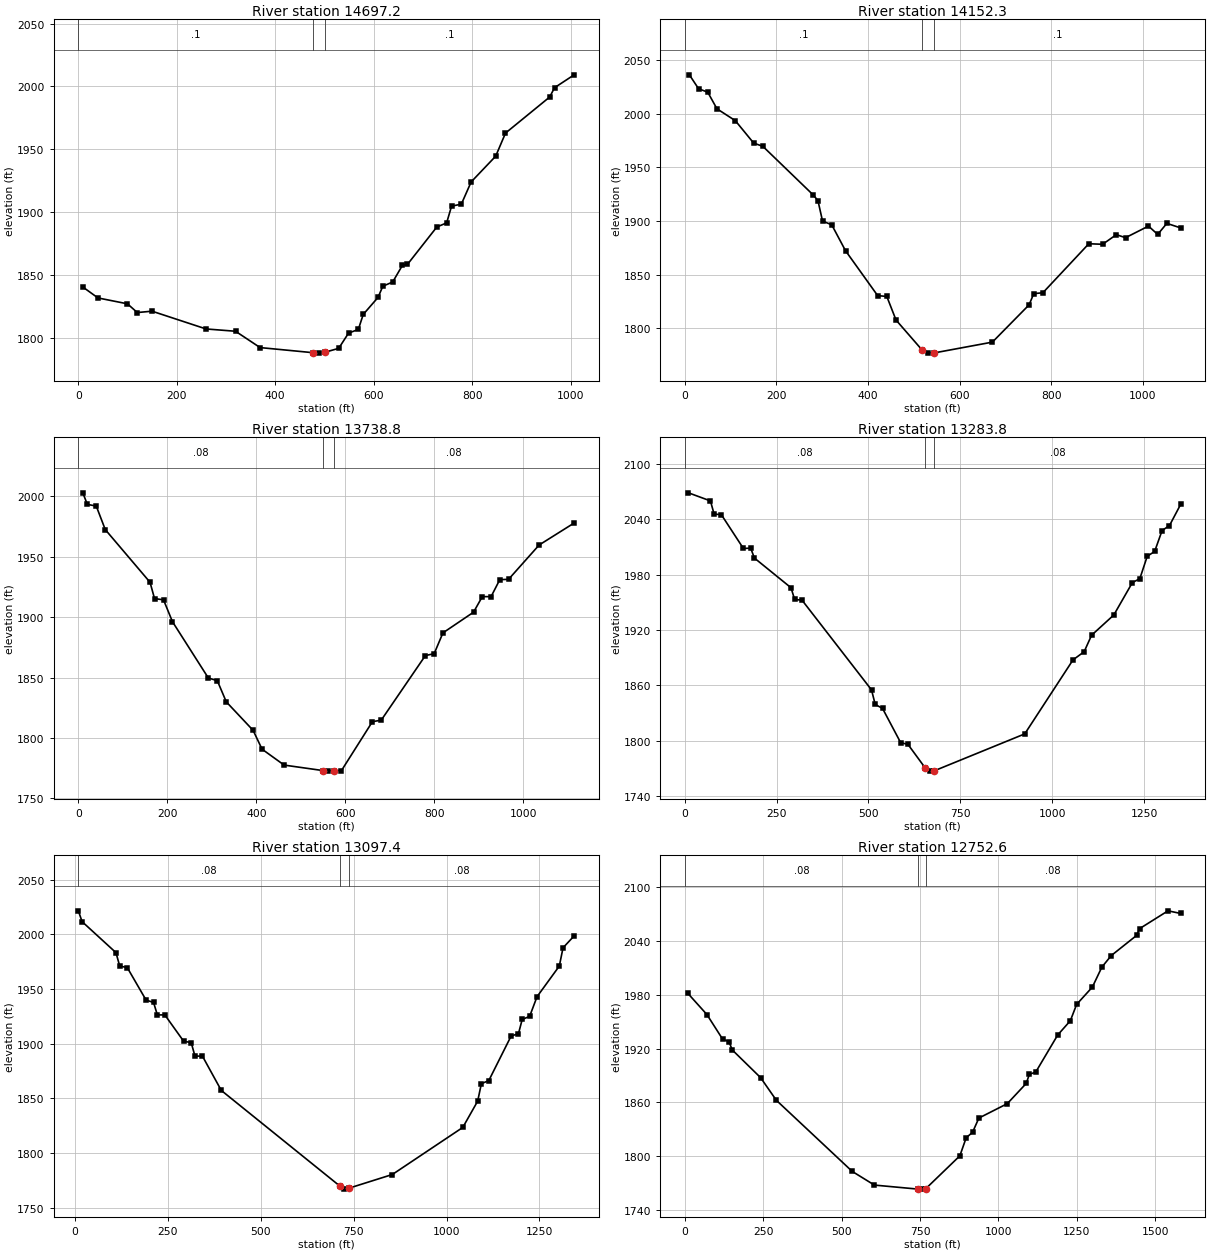
Type RM Length L Ch R = 1 ,14697.2 ,548.6,544.9,539.9
XS GIS Cut Line= 3
     1798773.928       91836.044     1798950.318       92302.956
     1799096.203       92789.896
#Sta/Elev= 30
      10 1840.19    39.9 1831.74    99.8 1827.06   119.8 1820.12   149.7  1821.2
   259.5 1807.07   319.4 1805.24   369.3 1792.25   476.6  1788.2   489.1 1787.84
   501.6 1788.61     529 1791.64     549 1803.75   568.9  1806.7   578.9 1818.65
   608.8  1832.1   618.7 1841.07   638.7 1844.41   658.6 1857.77   668.6 1858.37
   728.4 1888.17   748.3 1891.41   758.3 1904.73   778.2 1906.34   798.1    1924
     848 1944.51   867.9 1962.86   957.6 1991.53   967.6 1998.97  1007.4  2009.2
#Mann= 3 , 0 , 0
       0      .1       0   476.6    .045       0   501.6      .1       0
Bank Sta=476.6,501.6
XS Rating Curve= 0 ,0
Exp/Cntr=0.3,0.1

Type RM Length L Ch R = 1 ,14152.3 ,416.1,413.5,410.5
XS GIS Cut Line= 3
     1798183.129       91954.397     1798439.466       92408.506
     1798698.647       92906.528
#Sta/Elev= 30
      10 2036.17    30.1 2023.19    50.1 2020.02    70.2 2004.53   110.3 1993.47
   150.4 1972.58   170.5 1969.53   280.8 1924.09   290.8 1918.97   300.8  1899.9
   320.9 1896.43     351 1872.28   421.2 1830.44   441.2 1829.65   461.3 1807.69
     519 1779.39   531.5 1776.84     544 1776.99   671.8  1787.1     752 1821.86
   762.1 1832.27   782.1 1833.11   882.4 1878.77   912.5 1878.26   942.5 1887.22
   962.6 1884.42  1012.7 1895.22  1032.8 1887.46  1052.8 1897.75  1082.9 1893.54
#Mann= 3 , 0 , 0
       0      .1       0     519    .045       0     544      .1       0
Bank Sta=519,544
XS Rating Curve= 0 ,0
Exp/Cntr=0.3,0.1

Type RM Length L Ch R = 1 ,13738.8 ,437,455,469.8
XS GIS Cut Line= 4
      1797864.85        92243.44     1798077.921       92585.644
     1798304.118       92911.788     1798498.752       93159.027
#Sta/Elev= 30
    10.1 2003.02    20.2 1993.45    40.3 1992.07    60.5  1972.6   161.2 1928.95
   171.3 1915.45   191.5 1914.44   211.6 1896.33   292.3 1849.68   312.4  1847.5
   332.6 1829.95     393 1806.31     413 1790.76   462.7 1777.58   549.4 1773.07
   561.9 1772.58   574.4 1772.89   591.6 1773.06   661.1 1813.51     681  1814.8
   780.2 1868.25     800 1869.85   819.7 1887.06   888.5 1904.18   908.2 1917.07
   927.9 1917.04   947.5 1931.13   967.2 1931.39    1036 1959.83  1114.7 1978.03
#Mann= 3 , 0 , 0
       0     .08       0   549.4    .045       0   574.4     .08       0
Bank Sta=549.4,574.4
XS Rating Curve= 0 ,0
Exp/Cntr=0.3,0.1

Type RM Length L Ch R = 1 ,13283.8 ,213,186.4,162.5
XS GIS Cut Line= 4
     1797593.965       92112.209      1797793.86       92611.946
     1797762.297       92906.528     1798035.838        93343.14
#Sta/Elev= 30
      10 2068.57    69.8  2059.8    79.7 2045.61    99.7 2044.78   159.5 2008.25
   179.4  2008.6   189.4 1997.88   289.1 1965.68     299 1952.93     319 1952.25
   508.3 1854.91   518.3 1839.13   538.2 1834.88   587.6 1797.72   607.4 1795.87
   654.1 1770.48   666.6 1766.84   679.1 1767.19   925.4 1807.22  1056.8 1887.47
  1087.1 1896.32  1107.3 1914.16  1167.9 1936.17  1218.4 1971.29  1238.6 1975.45
  1258.8 1999.78    1279 2005.01  1299.2 2027.66  1319.4  2033.1  1349.7    2056
#Mann= 3 , 0 , 0
       0     .08       0   654.1    .045       0   679.1     .08       0
Bank Sta=654.1,679.1
XS Rating Curve= 0 ,0
Exp/Cntr=0.3,0.1

Type RM Length L Ch R = 1 ,13097.4 ,328,344.7,360.3
XS GIS Cut Line= 4
      1797394.07        92138.51     1797462.455       92680.331
     1797709.693       92896.007     1797893.807       93327.359
#Sta/Elev= 30
    10.1 2021.58    20.2 2011.69   111.2 1983.32   121.4 1971.02   141.6 1969.65
   192.2  1939.9   212.4 1937.69   222.5 1926.32   242.7 1926.28   293.3 1902.18
   313.5 1900.99   323.6 1888.69   343.9 1888.49   394.4 1857.19   712.6 1769.81
   725.1 1766.82   737.6 1767.68   854.3  1780.2  1043.8 1823.31  1083.8 1847.39
  1093.7 1863.34  1113.7 1866.19  1173.6  1906.9  1193.5 1909.19  1203.5 1922.14
  1223.5 1924.97  1243.4 1942.97  1303.3 1971.03  1313.3 1987.76  1343.2 1998.65
#Mann= 3 , 0 , 0
    10.1     .08       0   712.6    .045       0   737.6     .08       0
Bank Sta=712.6,737.6
XS Rating Curve= 0 ,0
Exp/Cntr=0.3,0.1

Type RM Length L Ch R = 1 ,12752.6 ,259.1,269.8,280.4
XS GIS Cut Line= 4
     1797283.602       92306.843     1797294.122       92769.758
     1797499.278       93274.755     1798025.317       93500.952
#Sta/Elev= 30
    10.1 1981.56    70.5 1958.04   120.8 1930.45   140.9 1927.87     151 1918.64
   241.6 1887.62   291.9 1862.29   533.7 1782.91   604.4 1767.63   743.3 1763.13
   755.8 1763.11   768.3 1763.63   876.9  1800.3   897.1 1820.53   917.3 1826.52
   937.5 1842.46  1028.2 1858.57  1088.5 1881.15  1098.5 1891.37  1118.6 1893.68
  1188.9 1935.25  1229.1 1951.14  1249.2 1969.39  1299.4 1988.74  1329.6    2011
  1359.7 2023.93  1440.1 2046.33  1450.1    2054  1540.5 2073.86  1580.7 2070.94
#Mann= 3 , 0 , 0
       0     .08       0   743.3    .045       0   768.3     .08       0
Bank Sta=743.3,768.3
XS Rating Curve= 0 ,0
Exp/Cntr=0.3,0.1

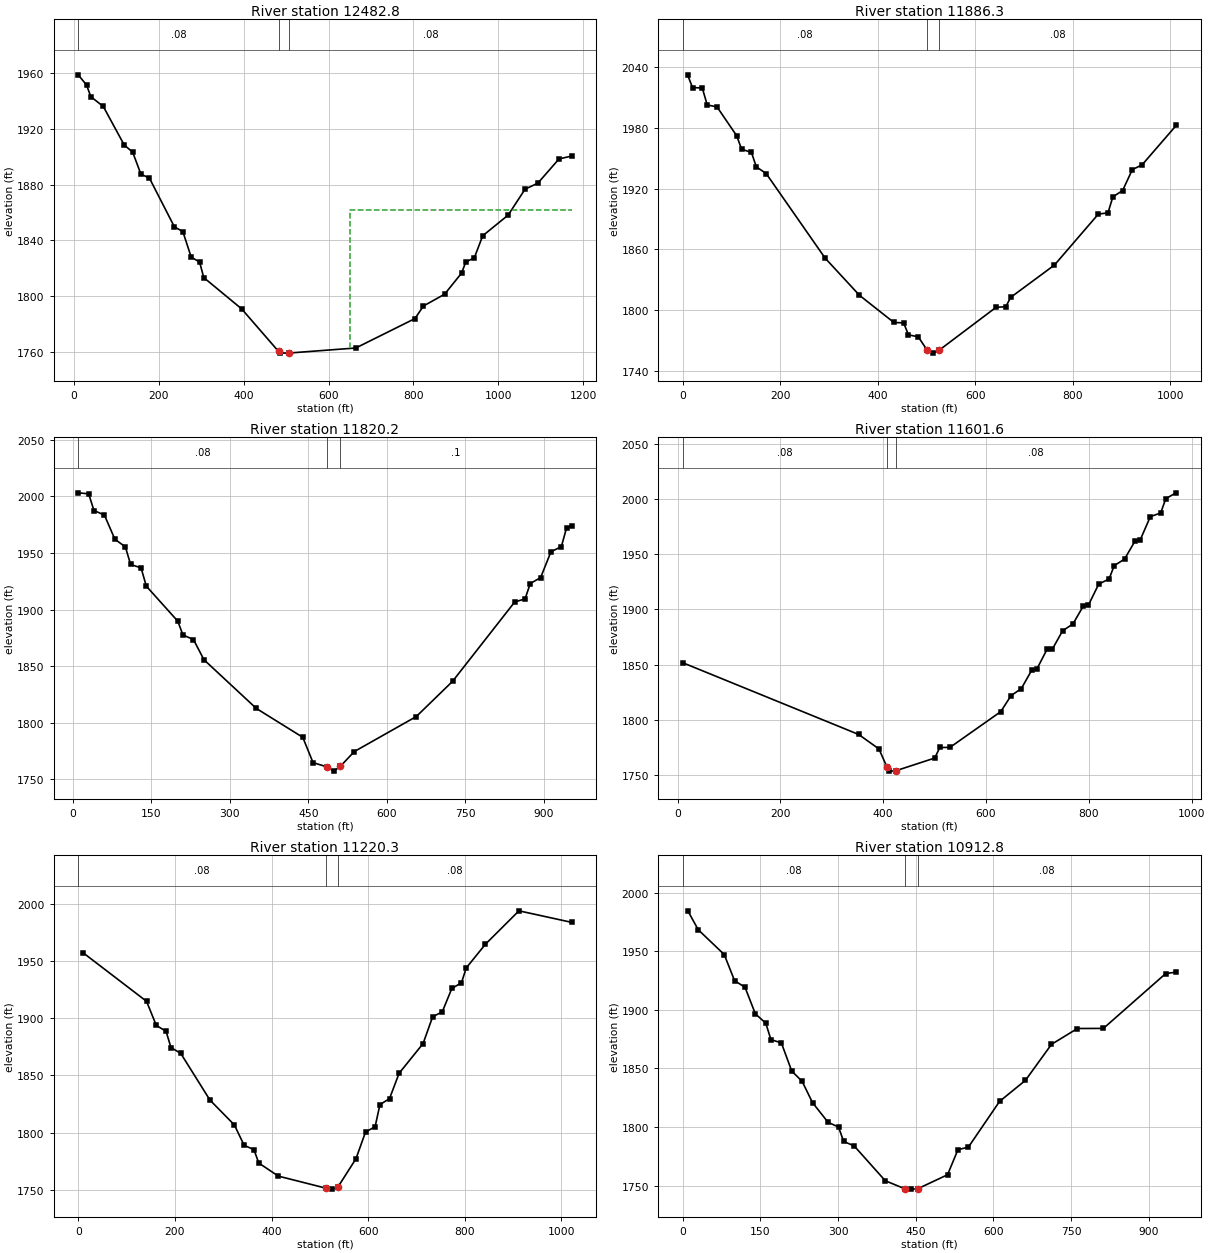
Type RM Length L Ch R = 1 ,12482.8 ,590.8,596.5,601.9
XS GIS Cut Line= 3
     1797019.527       92492.674     1797173.133       92790.799
     1797046.884        93606.16
#Sta/Elev= 30
     9.9 1958.73    29.6  1951.4    39.5  1943.1      69 1936.04   118.4 1908.39
   138.1 1903.38   157.8 1887.42   177.5 1884.82   236.7 1849.69   256.5 1846.38
   276.2 1828.02   295.9 1824.57   305.8 1813.38   395.1 1790.95   482.2  1760.4
   484.8 1759.23   507.2 1759.31   664.1 1762.91   803.5 1783.99   823.5 1792.99
   873.4 1801.47   913.4 1816.58   923.4 1824.63   943.3 1827.48   963.3 1843.38
  1023.2 1858.19  1063.1 1876.77  1093.1 1881.05    1143 1898.42    1173 1900.53
#Mann= 3 , 0 , 0
     9.9     .08       0   482.2    .045       0   507.2     .08       0
#XS Ineff= 2 , 0
                          651.21         1861.62
Permanent Ineff=
       F       F
Bank Sta=482.2,507.2
XS Rating Curve= 0 ,0
Exp/Cntr=0.3,0.1

Type RM Length L Ch R = 1 ,11886.3 ,61.7,66.1,70.6
XS GIS Cut Line= 3
     1796756.229       92481.255     1796673.396       92906.528
     1796524.635       93465.989
#Sta/Elev= 30
    10.1 2032.66    20.2 2020.08    40.3 2019.59    50.4 2002.86    70.5 2000.91
   110.8  1972.4   120.9 1959.07   141.1 1955.88   151.1  1941.6   171.3 1934.99
   292.2 1851.28   362.7 1814.47   433.3 1787.57   453.2  1787.2   463.2 1775.33
   483.2 1773.42   500.6 1760.81   513.1 1757.26   525.6 1759.98   642.9 1802.62
   662.8 1803.19   672.8 1812.44   762.6 1844.43   852.5  1894.8   872.4 1896.13
   882.4 1911.91   902.4 1918.16   922.3 1938.87   942.3 1943.56  1012.2 1982.52
#Mann= 3 , 0 , 0
       0     .08       0   500.6    .045       0   525.6     .08       0
Bank Sta=500.6,525.6
XS Rating Curve= 0 ,0
Exp/Cntr=0.3,0.1

Type RM Length L Ch R = 1 ,11820.2 ,236.6,218.6,200.7
XS GIS Cut Line= 4
     1796652.044        92489.96     1796641.443       92850.373
      1796548.69        93057.08     1796498.338       93420.142
#Sta/Elev= 30
      10 2003.12      30 2002.25    40.1  1987.5    60.1 1983.45    80.1 1962.12
   100.2 1955.34   110.2  1939.8   130.2 1936.83   140.2 1920.68   200.3 1889.77
   210.3 1877.53   230.4 1873.48   250.4 1855.68   350.6 1812.62   439.4 1787.12
   459.1 1764.72     486 1760.97   498.5 1757.24     511 1761.35   537.9 1774.51
   656.5 1805.48   725.8 1836.55   844.7  1906.7   864.5 1909.37   874.4 1922.98
   894.2  1928.2     914 1951.04   933.9 1955.59   943.8 1972.13   953.7 1973.91
#Mann= 3 , 0 , 0
      10     .08       0     486    .045       0     511      .1       0
Bank Sta=486,511
XS Rating Curve= 0 ,0
Exp/Cntr=0.3,0.1

Type RM Length L Ch R = 1 ,11601.6 ,385.4,381.3,378
XS GIS Cut Line= 4
     1796311.367       92504.186     1796342.564       92745.966
     1796420.558       93112.535     1796436.157       93463.505
#Sta/Elev= 30
     9.8 1851.79   352.3 1786.83   391.7 1773.72  407.45  1757.2   411.4 1753.66
   423.9  1753.9   500.2  1765.5   510.1 1775.06   529.8 1775.12   628.6 1807.47
   648.7 1821.97   668.7 1828.38   688.8 1844.91   698.9 1846.06   718.9 1864.03
     729 1864.01     749 1880.67   769.1 1886.85   789.2    1903   799.2 1903.87
   819.3 1922.95   839.4 1927.52   849.4 1939.61   869.5 1945.53   889.6 1961.67
   899.6 1962.49   919.7 1983.99   939.8 1987.27   949.8 2000.29   969.9 2005.51
#Mann= 3 , 0 , 0
     9.8     .08       0  407.45    .045       0   423.9     .08       0
Bank Sta=407.45,423.9
XS Rating Curve= 0 ,0
Exp/Cntr=0.3,0.1

Type RM Length L Ch R = 1 ,11220.3 ,307.4,307.4,306.7
XS GIS Cut Line= 3
     1795870.437       92625.297     1796057.015       93116.175
     1796220.922       93584.471
#Sta/Elev= 30
    10.1 1957.09   141.4  1914.7   161.6 1893.65   181.8 1888.53   191.9 1874.34
   212.1 1869.28   272.7 1828.43   323.2 1806.74   343.4 1788.92   363.6  1785.2
   373.7 1773.47   414.1 1762.07   512.6 1751.54   525.1  1750.7   537.6 1752.63
   574.8 1777.24   594.6 1800.57   614.4 1805.18   624.4 1824.53   644.2  1829.7
   664.1 1851.87   713.7 1877.83   733.5 1901.21   753.4 1905.54   773.2 1925.92
   793.1 1930.87     803 1943.84   842.7 1964.56   912.1 1993.72  1021.3 1983.64
#Mann= 3 , 0 , 0
       0     .08       0   512.6    .045       0   537.6     .08       0
Bank Sta=512.6,537.6
XS Rating Curve= 0 ,0
Exp/Cntr=0.3,0.1

Type RM Length L Ch R = 1 ,10912.8 ,290.2,292.2,293.1
XS GIS Cut Line= 2
     1795609.426       92784.963     1795952.597       93674.088
#Sta/Elev= 30
      10 1984.46    30.1 1968.32    80.3 1947.18   100.3 1924.84   120.4 1919.29
   140.4 1896.59   160.5 1888.63   170.5 1874.58   190.6 1871.82   210.7 1847.75
   230.7 1839.02   250.8 1820.85   280.9 1804.03     301 1800.02     311 1787.69
   331.1 1783.97   391.3  1754.2   428.9 1747.37   441.4 1747.04   453.9 1747.32
   511.6 1759.32   531.7 1780.71   551.8 1782.85     612 1821.85   662.1 1839.88
   712.3 1870.55   762.4 1884.07   812.6 1884.15     933 1930.98   953.1 1932.14
#Mann= 3 , 0 , 0
       0     .08       0   428.9    .045       0   453.9     .08       0
Bank Sta=428.9,453.9
XS Rating Curve= 0 ,0
Exp/Cntr=0.3,0.1

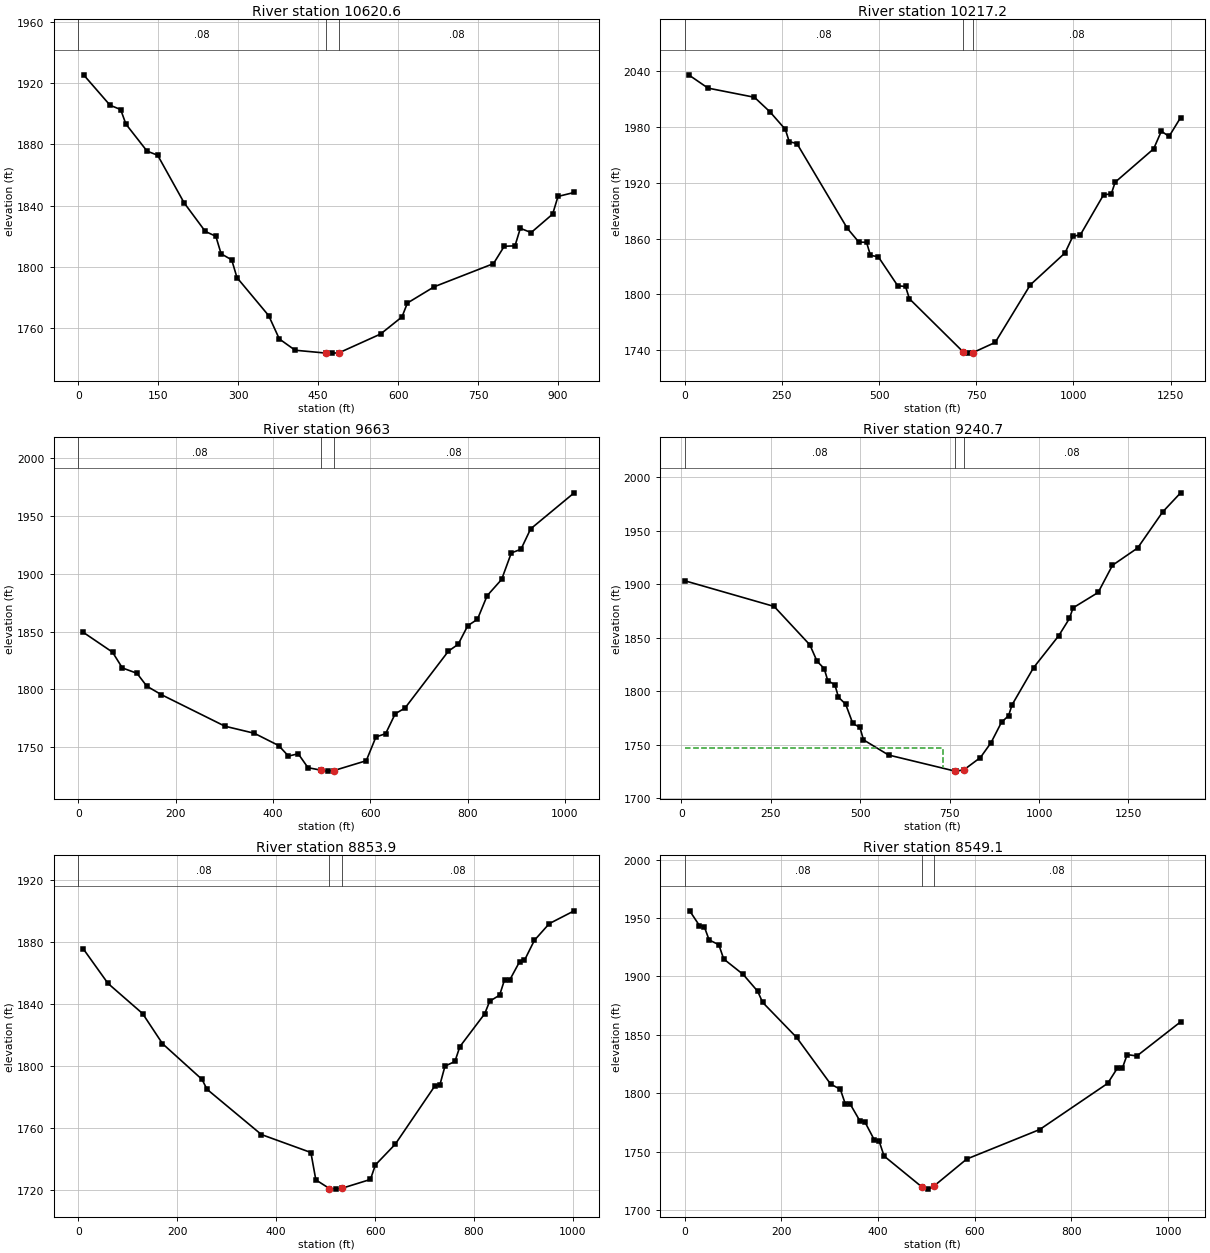
Type RM Length L Ch R = 1 ,10620.6 ,395.5,403.4,412.4
XS GIS Cut Line= 3
     1795395.121       92890.747     1795531.003       93357.604
     1795668.661       93779.753
#Sta/Elev= 30
     9.9 1925.44    59.5 1905.58    79.4 1902.76    89.3 1893.24     129 1875.58
   148.8 1872.94   198.5 1841.82   238.2 1823.16     258 1819.99   267.9 1808.55
   287.8 1804.57   297.7 1792.96   357.2 1768.13   377.1 1752.92   406.8 1745.55
   463.8 1743.71   476.3 1743.66   488.8 1743.83     567 1756.12   607.3 1767.34
   617.4 1776.38   667.9 1787.04   778.9 1802.11   799.1 1813.46   819.3 1813.74
   829.3 1825.22   849.5 1822.38   889.9 1834.46     900 1846.01   930.3  1848.6
#Mann= 3 , 0 , 0
       0     .08       0   463.8    .045       0   488.8     .08       0
Bank Sta=463.8,488.8
XS Rating Curve= 0 ,0
Exp/Cntr=0.3,0.1

Type RM Length L Ch R = 1 ,10217.2 ,574.2,554.2,532
XS GIS Cut Line= 4
     1795274.132       92690.852     1795137.361       93137.985
     1795132.101       93569.337     1795310.954       93900.742
#Sta/Elev= 30
     9.9 2036.26    59.7 2021.96   179.1  2012.1   218.9 1996.49   258.7 1977.49
   268.6  1964.3   288.5 1962.24   417.8 1871.15   447.7 1856.16   467.6 1855.91
   477.6 1841.83   497.7 1840.39   547.8 1809.11   567.9 1808.35   577.9 1795.09
   715.9 1738.02   728.4 1736.59   740.9 1737.07   798.6 1748.13   888.9 1810.11
   978.2 1844.49   998.1 1862.19  1017.9 1864.12  1077.4 1907.11  1097.2 1907.99
  1107.1 1920.63  1206.2 1956.55    1226 1975.58  1245.8 1969.92  1275.6 1990.23
#Mann= 3 , 0 , 0
       0     .08       0   715.9    .045       0   740.9     .08       0
Bank Sta=715.9,740.9
XS Rating Curve= 0 ,0
Exp/Cntr=0.3,0.1

Type RM Length L Ch R = 1 ,9663    ,423.2,422.3,423.6
XS GIS Cut Line= 3
     1794289.985        93053.82      1794614.81       93462.572
     1794959.695       93819.998
#Sta/Elev= 30
      10 1849.37    70.3 1832.15    90.4 1818.53   120.5 1813.89   140.6 1802.78
   170.7 1795.39   301.2 1768.12   361.5 1762.02   411.7 1751.36   431.7 1742.28
   451.8 1744.26   471.9 1732.24   499.6 1729.99   512.1 1729.25   524.6 1729.66
   591.6 1738.25   611.5 1758.81   631.4 1761.65   651.2 1778.92   671.1 1783.75
   760.5 1833.09   780.4 1838.96   800.2 1855.06   820.1 1860.62     840 1881.03
   869.8 1895.11   889.7 1918.05   909.5 1921.19   929.4 1938.85  1018.8 1970.03
#Mann= 3 , 0 , 0
       0     .08       0   499.6    .045       0   524.6     .08       0
Bank Sta=499.6,524.6
XS Rating Curve= 0 ,0
Exp/Cntr=0.3,0.1

Type RM Length L Ch R = 1 ,9240.7  ,402.8,386.8,371.6
XS GIS Cut Line= 4
     1794188.578       92985.434     1794235.921       93642.983
     1794404.254       93848.138     1794856.648       93979.648
#Sta/Elev= 30
      10 1903.31   259.7 1879.27   359.6 1843.27   379.6 1827.98   399.5 1821.15
   409.5 1809.92   429.5 1805.86   439.5 1794.27   459.5 1787.79   479.5 1769.77
   499.4    1766   509.4 1754.39   579.3  1740.2   764.7 1725.16   767.4 1725.11
   789.7 1726.26   836.2 1737.84   865.7 1751.66   895.1 1770.85   914.8 1776.98
   924.6 1787.18   984.8    1822  1054.9 1851.78    1085 1868.04    1095 1877.94
  1165.2 1892.35  1205.3 1917.83  1275.5 1933.97  1345.6 1967.77  1395.7 1985.63
#Mann= 3 , 0 , 0
      10     .08       0   764.7    .045       0   789.7     .08       0
#XS Ineff= 2 , 0
          732.86 1746.87
Permanent Ineff=
       F       F
Bank Sta=764.7,789.7
XS Rating Curve= 0 ,0
Exp/Cntr=0.3,0.1

Type RM Length L Ch R = 1 ,8853.9  ,307.5,304.8,301.2
XS GIS Cut Line= 3
     1793621.571       93882.758     1794100.105        94028.32
     1794568.034       94210.919
#Sta/Elev= 30
      10 1875.31      60 1852.99     130 1833.53   170.1 1814.16   250.1 1791.08
   260.1 1784.72   370.1 1755.51   470.2 1743.91   480.2 1726.27   507.8 1720.65
   520.3 1720.29   532.8 1720.82   590.6 1726.54   600.6  1735.9   640.8 1749.27
   721.2 1787.03   731.2 1787.76   741.3 1799.63   761.4 1802.65   771.4 1812.21
   821.7 1833.46   831.7 1841.53   851.8 1845.43   861.8 1855.43   871.9 1855.03
     892  1866.9     902 1867.89   922.1 1880.81   952.2 1891.58  1002.5 1899.84
#Mann= 3 , 0 , 0
       0     .08       0   507.8    .045       0   532.8     .08       0
Bank Sta=507.8,532.8
XS Rating Curve= 0 ,0
Exp/Cntr=0.3,0.1

Type RM Length L Ch R = 1 ,8549.1  ,291.4,295.3,297.9
XS GIS Cut Line= 2
     1793548.723       94200.584     1794542.937       94453.083
#Sta/Elev= 30
    10.1 1956.14    30.2 1943.56    40.2 1942.67    50.3 1931.24    70.4  1927.1
    80.5 1914.88   120.7 1901.69   150.8 1887.26   160.9  1877.8   231.3 1847.72
   301.7 1807.78   321.8 1803.29   331.9 1790.97   341.9 1790.82     362 1776.41
   372.1 1775.72   392.2 1759.84   402.3  1758.6   412.3 1746.13   490.3 1719.75
   502.8 1717.81   515.3 1720.38   583.3 1743.58   734.1 1768.82   874.9 1808.39
     895 1821.48   905.1 1821.22   915.2 1833.01   935.3 1831.85  1025.8 1861.08
#Mann= 3 , 0 , 0
       0     .08       0   490.3    .045       0   515.3     .08       0
Bank Sta=490.3,515.3
XS Rating Curve= 0 ,0
Exp/Cntr=0.3,0.1

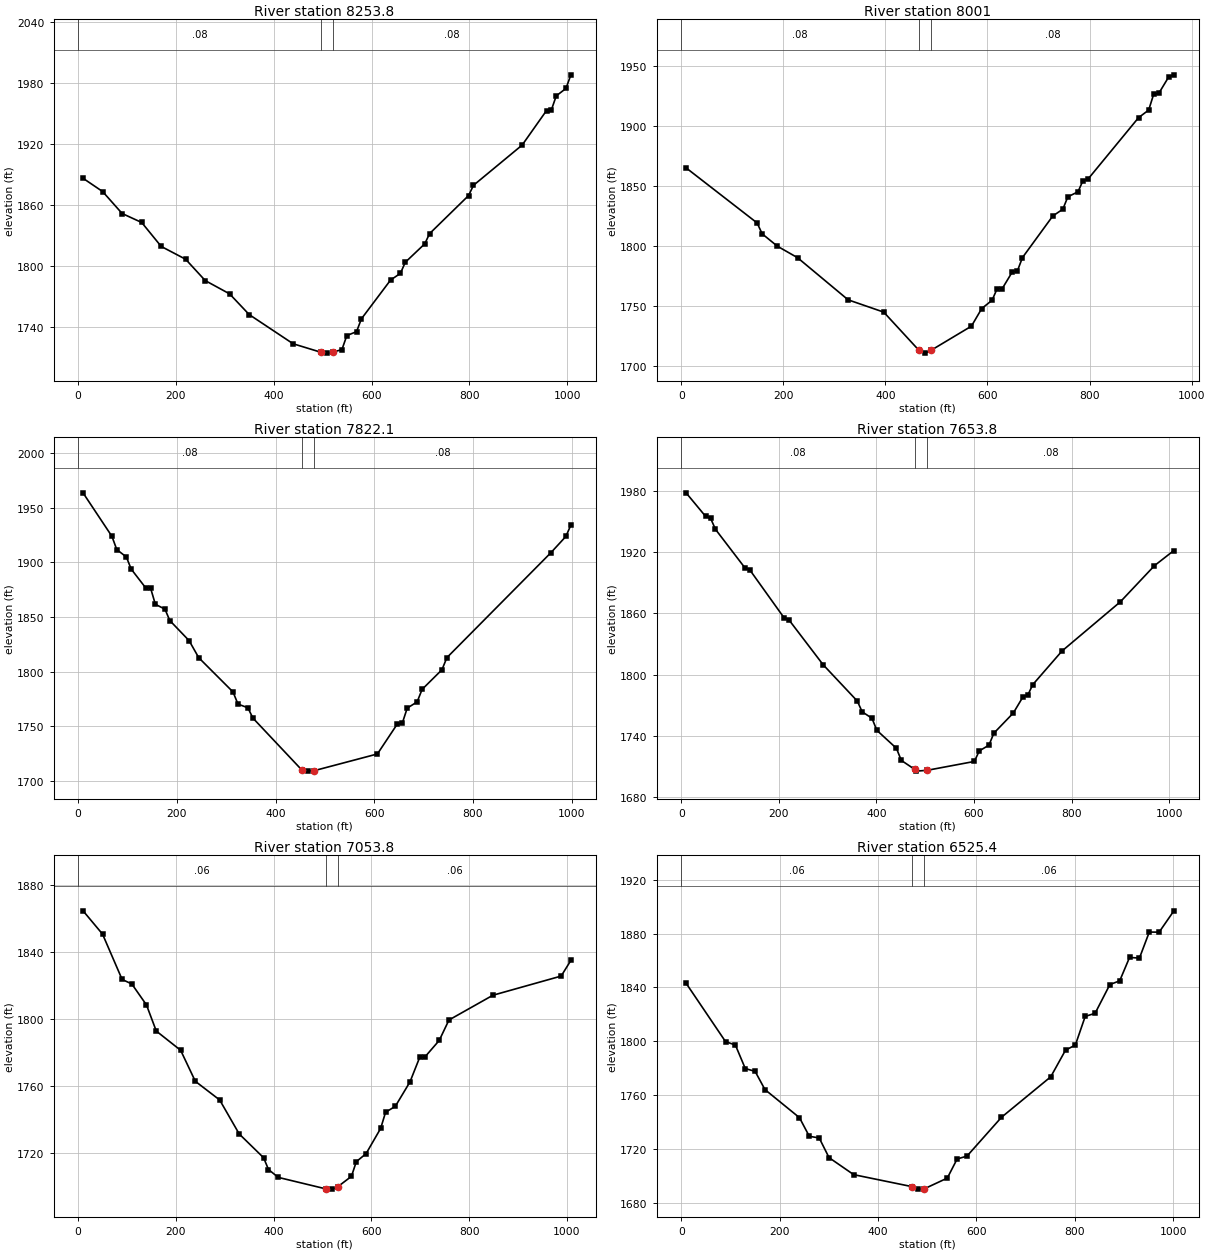
Type RM Length L Ch R = 1 ,8253.8  ,251.8,252.9,255.2
XS GIS Cut Line= 3
     1793522.421          94411.     1794003.676       94606.671
     1794464.031       94768.707
#Sta/Elev= 30
      10 1886.37      50 1873.32    89.9 1851.69   129.9 1842.86   169.8 1819.28
   219.8 1806.64   259.8 1785.66   309.7 1772.56   349.7 1752.19   439.6 1723.42
     497 1714.98   509.5 1714.21     522 1715.32   539.4 1717.71   549.4 1731.48
   569.3 1735.37   579.3 1748.03     639 1786.25     659 1792.72   668.9 1803.63
   708.8 1821.86   718.7  1831.9   798.4 1869.37   808.4 1879.45     908  1919.1
   957.8 1953.08   967.7 1953.64   977.7 1967.52   997.6 1974.88  1007.6 1988.26
#Mann= 3 , 0 , 0
       0     .08       0     497    .045       0     522     .08       0
Bank Sta=497,522
XS Rating Curve= 0 ,0
Exp/Cntr=0.3,0.1

Type RM Length L Ch R = 1 ,8001    ,180.3,178.8,177.3
XS GIS Cut Line= 4
     1793422.473       94705.582     1793790.701       94784.488
     1794011.637       94884.435     1794343.042       94984.383
#Sta/Elev= 30
     9.9 1865.25   148.7 1819.46   158.6  1810.4   188.3  1800.1   227.9 1790.51
     327 1755.39   396.8 1745.14   465.1 1713.62   477.6 1710.98   490.1 1713.48
   568.6 1733.47   588.8 1748.15     609 1755.03   619.1  1764.8     629  1764.8
   648.7  1778.7   658.6 1779.48   668.5 1790.57   727.9 1825.22   747.6  1830.9
   757.5 1841.24   777.3  1845.4   787.2  1854.8   797.1 1856.07     896 1907.19
   915.8 1913.51   925.7 1926.89   935.6 1927.44   955.3  1941.3   965.2 1942.87
#Mann= 3 , 0 , 0
       0     .08       0   465.1    .045       0   490.1     .08       0
Bank Sta=465.1,490.1
XS Rating Curve= 0 ,0
Exp/Cntr=0.3,0.1

Type RM Length L Ch R = 1 ,7822.1  ,175.3,168.3,160.7
XS GIS Cut Line= 4
     1793339.817       94875.187     1793620.593       94914.183
     1793940.366       95038.973     1794306.936       95101.368
#Sta/Elev= 30
     9.8 1963.63    68.4 1923.82    78.2 1911.76    97.7 1904.89   107.5 1893.83
   136.8  1876.7   146.6  1876.7   156.4 1861.67   175.9  1857.2   185.7 1846.79
   224.8 1828.42   244.4 1812.78   313.8 1781.47   323.9 1770.37     344 1766.96
   354.1 1757.58   452.7 1710.36   465.2 1709.03   477.7 1709.37   606.5 1724.74
   646.8 1752.12   656.9 1752.88   666.9 1766.66     687 1772.39   697.1 1783.82
   737.3 1801.78   747.3 1812.85   958.4 1908.99   988.5 1923.75   998.6 1934.16
#Mann= 3 , 0 , 0
       0     .08       0   452.7    .045       0   477.7     .08       0
Bank Sta=452.7,477.7
XS Rating Curve= 0 ,0
Exp/Cntr=0.3,0.1

Type RM Length L Ch R = 1 ,7653.8  ,591.8,600,610.7
XS GIS Cut Line= 3
     1793290.963       95094.851     1793779.133       95149.675
     1794295.698       95194.799
#Sta/Elev= 30
      10 1978.01    50.1 1954.92    60.2 1953.12    70.2 1942.32   130.3 1904.79
   140.4 1902.73   210.5 1855.93   220.6 1853.82   290.7  1809.9   360.9 1774.25
   370.9 1763.73     391 1757.37     401 1745.59   441.1 1728.01   451.1 1716.17
   478.7 1707.34   481.2 1705.66   503.7 1706.43   600.9 1715.14   610.9 1725.44
   630.8 1731.09   640.8  1742.8   680.7 1762.55   700.6 1778.43   710.6 1780.31
   720.6 1790.32   780.4 1823.17   900.1 1871.37   969.9  1906.7  1009.8 1921.57
#Mann= 3 , 0 , 0
       0     .08       0   478.7    .045       0   503.7     .08       0
Bank Sta=478.7,503.7
XS Rating Curve= 0 ,0
Exp/Cntr=0.3,0.1

Type RM Length L Ch R = 1 ,7053.8  ,515,528.4,539.1
XS GIS Cut Line= 3
     1793280.204       95488.569     1793743.898       95699.155
     1794182.173       95937.626
#Sta/Elev= 30
      10  1864.5    49.9 1850.59    89.9  1823.6   109.8 1820.88   139.8 1808.38
   159.8 1792.84   209.7 1781.35   239.7 1762.88   289.6 1751.73   329.5 1731.49
   379.5 1717.28   389.4 1710.29   409.4 1705.59   506.8 1698.74   519.3 1698.59
   531.8 1700.15   559.2 1706.21   569.1 1714.94   589.1 1719.73     619  1734.8
     629 1744.41     649 1747.96   678.9 1762.48   698.9 1777.17   708.9 1777.17
   738.8 1787.22   758.7 1799.41   848.6 1814.17   988.3  1825.6  1008.2 1834.94
#Mann= 3 , 0 , 0
       0     .06       0   506.8    .045       0   531.8     .06       0
Bank Sta=506.8,531.8
XS Rating Curve= 0 ,0
Exp/Cntr=0.3,0.1

Type RM Length L Ch R = 1 ,6525.4  ,556.8,550.1,544.8
XS GIS Cut Line= 3
     1793074.687       95658.492     1793386.993       96049.782
     1793707.606       96434.077
#Sta/Elev= 30
      10 1843.13    90.1 1799.73   110.1 1797.21   130.2 1779.71   150.2  1777.6
   170.2 1764.05   240.3 1743.16   260.3  1729.3   280.4 1728.08   300.4 1713.43
   350.5 1700.77   468.1 1691.92   480.6    1690   493.1 1690.09   540.7 1698.22
   560.7 1712.45   580.7 1714.56   650.8 1743.45   750.9 1773.57   780.9 1793.38
   800.9 1797.19   820.9 1818.49     841 1820.81     871 1842.17     891 1844.97
     911 1862.36   931.1 1861.87   951.1 1881.23   971.1 1881.16  1001.1 1897.03
#Mann= 3 , 0 , 0
       0     .06       0   468.1    .045       0   493.1     .06       0
Bank Sta=468.1,493.1
XS Rating Curve= 0 ,0
Exp/Cntr=0.3,0.1

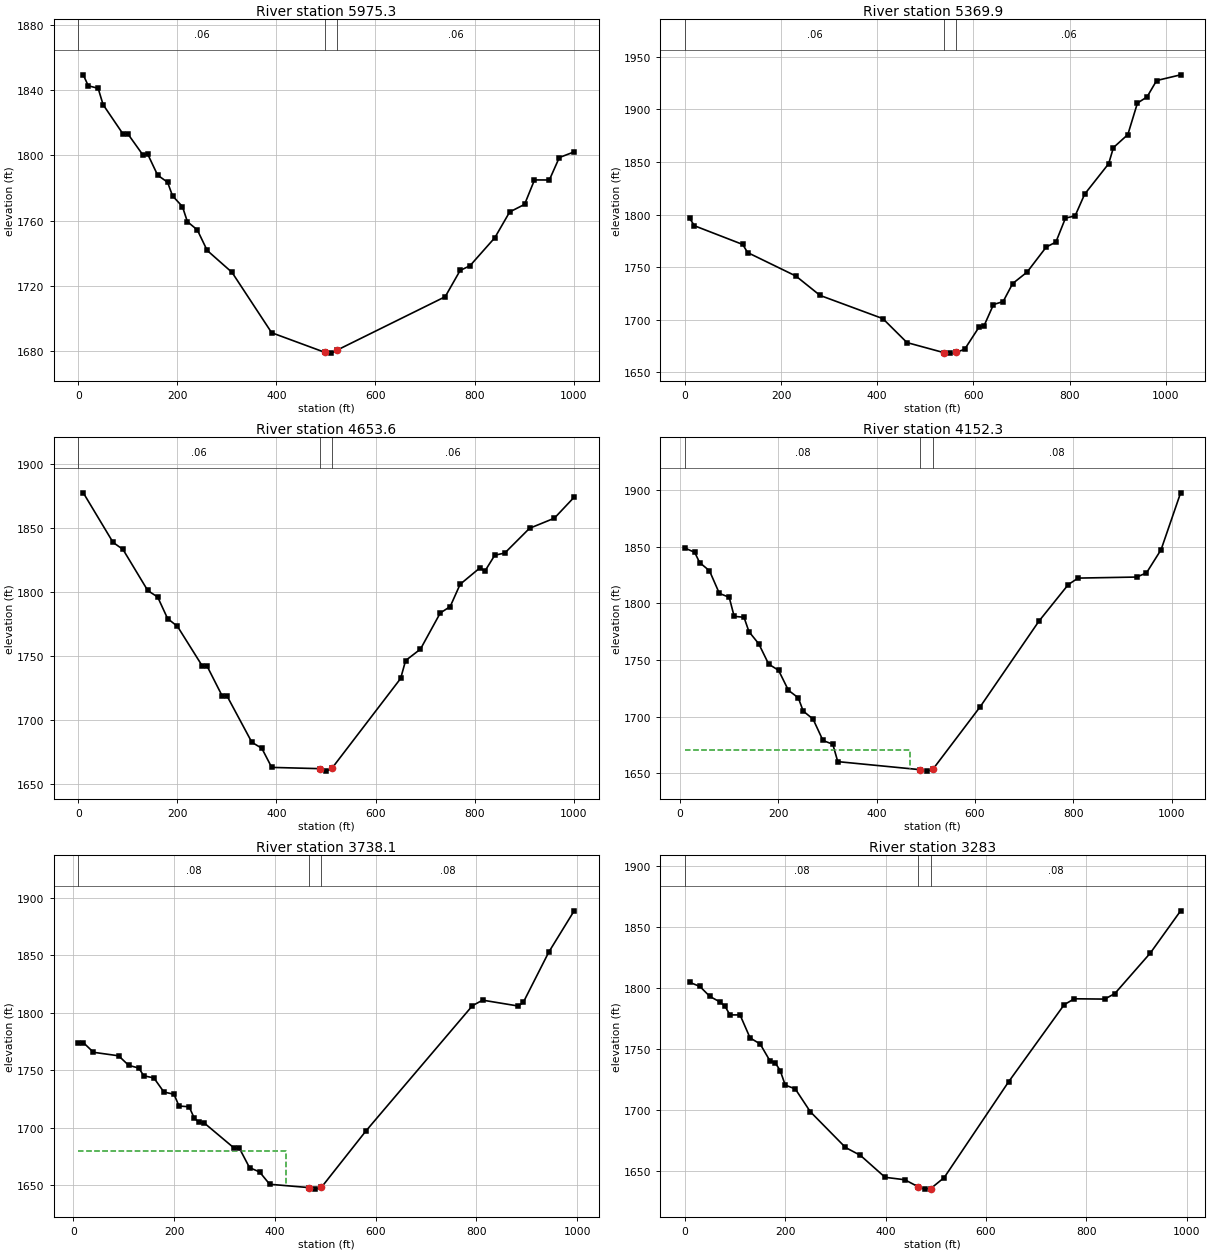
Type RM Length L Ch R = 1 ,5975.3  ,604.3,605.4,605.6
XS GIS Cut Line= 3
     1792572.591       96100.774     1792970.258       96404.611
     1793359.252       96719.945
#Sta/Elev= 30
      10 1849.31      20  1842.6      40 1841.06      50 1831.04    90.1  1813.1
   100.1 1813.09   130.1 1800.32   140.1 1800.69   160.1 1787.84   180.2 1783.49
   190.2 1775.15   210.2 1768.58   220.2 1759.33   240.2 1754.31   260.2 1741.69
   310.3 1728.27   390.4 1691.27     498 1679.23   510.5 1678.78     523  1680.7
   740.8 1713.34   770.9 1729.42   790.9 1732.34     841  1749.5     871 1765.28
   901.1 1769.93   921.1 1784.91   951.1 1784.87   971.2 1798.62  1001.2  1802.1
#Mann= 3 , 0 , 0
       0     .06       0     498    .045       0     523     .06       0
Bank Sta=498,523
XS Rating Curve= 0 ,0
Exp/Cntr=0.3,0.1

Type RM Length L Ch R = 1 ,5369.9  ,716.6,716.3,716
XS GIS Cut Line= 3
     1792223.104       96515.157     1792604.421       96856.968
     1792989.493       97204.293
#Sta/Elev= 30
      10 1796.53    20.1 1789.44   120.5 1771.66   130.5    1764   230.9 1741.67
   281.1 1723.26   411.7 1701.18   461.9  1678.4   539.5 1668.73     552 1668.38
   564.5 1669.06   581.9 1672.16   611.8 1693.21   621.8 1694.11   641.7 1714.58
   661.7 1717.37   681.6 1734.55   711.5 1745.39   751.4 1769.25   771.4 1773.91
   791.3 1796.76   811.3  1798.8   831.2 1819.49   881.1 1848.43     891 1863.74
     921 1876.17   940.9 1906.06   960.9 1911.94   980.8 1927.49  1030.7 1932.93
#Mann= 3 , 0 , 0
       0     .06       0   539.5    .045       0   564.5     .06       0
Bank Sta=539.5,564.5
XS Rating Curve= 0 ,0
Exp/Cntr=0.3,0.1

Type RM Length L Ch R = 1 ,4653.6  ,484.6,501.4,518.8
XS GIS Cut Line= 3
     1791785.208       97102.859     1792174.551       97417.362
     1792563.895       97731.864
#Sta/Elev= 30
      10 1877.74    70.1 1838.93    90.1 1833.44   140.1 1801.28   160.2 1796.15
   180.2 1779.31   200.2 1773.16   250.2 1742.21   260.3 1741.79   290.3 1718.83
   300.3 1718.62   350.3 1682.47   370.4 1677.76   390.4  1662.8     488 1661.81
   500.5 1659.88     513 1662.62   650.7 1732.42   660.7 1746.43   690.7 1755.37
   730.7 1783.68   750.7 1788.68   770.8 1806.14   810.8 1819.01   820.8 1816.44
   840.8 1828.94   860.9 1830.58   910.9 1849.96     961 1857.87    1001 1874.33
#Mann= 3 , 0 , 0
       0     .06       0     488    .045       0     513     .06       0
Bank Sta=488,513
XS Rating Curve= 0 ,0
Exp/Cntr=0.3,0.1

Type RM Length L Ch R = 1 ,4152.3  ,413.1,414.2,414.3
XS GIS Cut Line= 3
     1791686.093       97280.106     1791833.366       97780.611
     1791946.155       98264.337
#Sta/Elev= 30
      10  1848.7    30.1 1844.93    40.1 1835.91    60.2 1828.62    80.3 1808.66
   100.3 1805.27   110.4 1788.42   130.4 1787.62   140.5 1774.91   160.5 1764.14
   180.6 1746.27   200.7 1740.83   220.7 1723.22   240.8 1716.54   250.8 1704.88
   270.9 1697.74     291  1678.9     311 1675.59   321.1 1660.25   489.2 1653.13
   501.7 1651.87   514.2 1653.31   611.1 1708.87   730.3 1784.23   789.9 1816.44
   809.8 1822.18     929  1823.1   948.9 1826.74   978.7 1847.29  1018.4 1897.41
#Mann= 3 , 0 , 0
      10     .08       0   489.2    .045       0   514.2     .08       0
#XS Ineff= 2 , 0
          468.35 1670.17
Permanent Ineff=
       F       F
Bank Sta=489.2,514.2
XS Rating Curve= 0 ,0
Exp/Cntr=0.3,0.1

Type RM Length L Ch R = 1 ,3738.1  ,461.5,455.1,449
XS GIS Cut Line= 3
     1791310.451       97354.182     1791432.372       97838.643
     1791557.689       98316.833
#Sta/Elev= 30
      10 1773.75      20 1773.92      40 1765.51    89.9 1762.47   109.9 1754.14
   129.9  1751.8   139.9 1745.04   159.9  1743.2   179.8  1730.9   199.8    1729
   209.8 1718.72   229.8  1718.1   239.8 1708.43   249.8 1704.44   259.8 1703.96
   319.7 1681.91   329.7 1681.89   349.7 1665.09   369.7 1661.32   389.7  1650.6
   467.1 1647.73   479.6 1646.37   492.1 1647.79   580.3  1696.8   792.1 1806.12
   812.3 1810.91   882.9 1805.81     893 1809.02   943.5 1852.71   993.9 1888.69
#Mann= 3 , 0 , 0
      10     .08       0   467.1    .045       0   492.1     .08       0
#XS Ineff= 2 , 0
           422.5 1679.22
Permanent Ineff=
       F       F
Bank Sta=467.1,492.1
XS Rating Curve= 0 ,0
Exp/Cntr=0.3,0.1

Type RM Length L Ch R = 1 ,3283    ,244.6,254.4,264.2
XS GIS Cut Line= 4
     1790784.818       97549.529     1790940.099       97852.194
     1791071.692       98104.854     1791334.879       98354.882
#Sta/Elev= 30
      10 1804.52      30 1801.22      50 1792.99      70 1788.54      80 1785.06
      90 1777.88   110.1 1777.88   130.1 1759.03   150.1 1754.11   170.1 1739.96
   180.1 1738.65   190.1 1732.33   200.1 1720.37   220.1 1717.28   250.1 1698.57
   320.2 1669.28     350 1662.79   399.1 1644.83   438.4 1642.83   465.2 1637.06
   477.7 1635.14   490.2 1635.62     517 1644.64   645.2 1723.03   756.1 1786.28
   776.3  1791.1   836.8 1790.84     857 1795.37   927.6 1828.51   988.1 1863.16
#Mann= 3 , 0 , 0
       0     .08       0   465.2    .045       0   490.2     .08       0
Bank Sta=465.2,490.2
XS Rating Curve= 0 ,0
Exp/Cntr=0.3,0.1

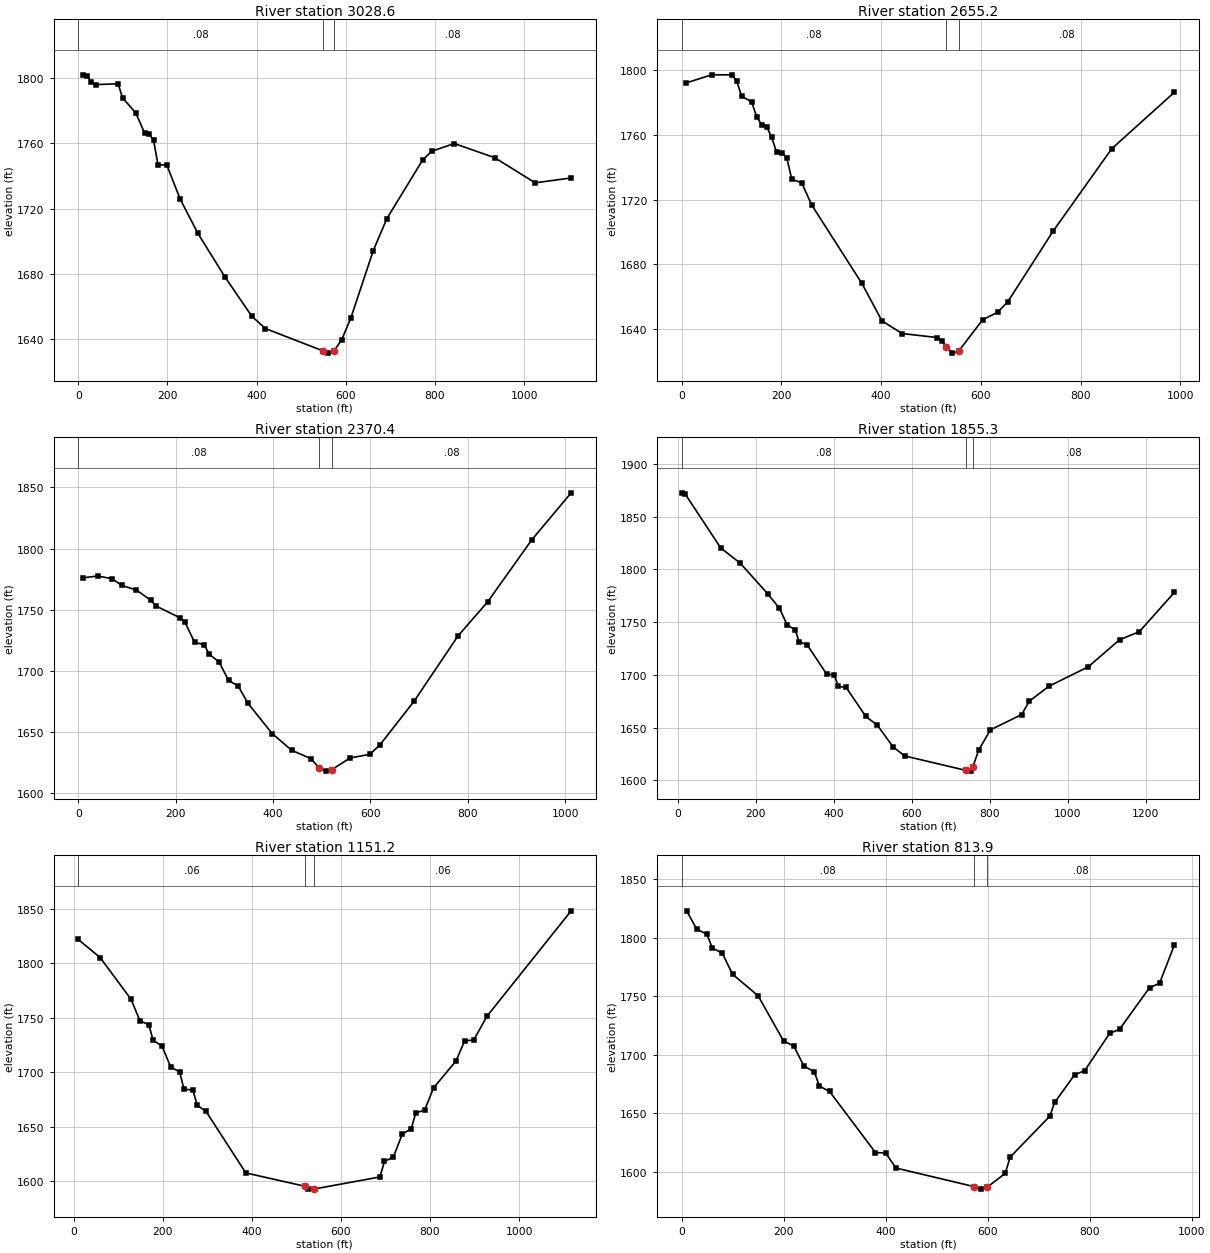
Type RM Length L Ch R = 1 ,3028.6  ,359.2,373.4,387.5
XS GIS Cut Line= 4
     1790625.303       97568.406     1790744.933       97819.735
     1790797.537       98230.045      1790614.97       98600.841
#Sta/Elev= 30
     9.9 1801.95    19.9 1801.22    29.8 1797.48    39.8 1795.97    89.5 1796.45
    99.4 1787.92   129.2 1778.54   149.1 1766.16   159.1 1765.63     169 1761.79
   178.9 1746.95   198.8 1746.51   228.6 1725.86   268.4 1704.75   328.8 1678.15
   389.3 1653.97   419.6 1646.44   548.4 1632.77   560.9 1631.35   573.4  1632.5
   591.1  1639.7   611.3 1652.84   661.7 1694.25     692 1713.78   772.7  1749.9
   792.8 1755.07   843.2 1759.84     934 1751.14  1024.7 1735.76  1105.3 1738.73
#Mann= 3 , 0 , 0
       0     .08       0   548.4    .045       0   573.4     .08       0
Bank Sta=548.4,573.4
XS Rating Curve= 0 ,0
Exp/Cntr=0.3,0.1

Type RM Length L Ch R = 1 ,2655.2  ,283.7,284.8,286.7
XS GIS Cut Line= 4
     1790493.056       97511.365     1790469.658        97932.53
      1790337.07       98260.102     1790235.678       98447.286
#Sta/Elev= 30
      10 1792.35    60.3  1797.3   100.4  1797.3   110.5 1793.61   120.5 1784.03
   140.6 1780.54   150.6 1771.32   160.7 1766.43   170.7 1765.22   180.8  1758.5
   190.8 1749.19   200.9 1749.12   210.9 1745.93     221  1732.7     241 1730.31
   261.1 1716.62   361.6 1668.06   401.7 1644.91     442 1637.02   512.7 1634.53
   522.8 1632.44   530.5 1628.95     543 1624.88   555.5 1626.09   603.6 1645.56
   633.8 1650.24     654 1656.68   744.9 1700.47   862.3 1751.49   988.1 1786.53
#Mann= 3 , 0 , 0
       0     .08       0   530.5    .045       0   555.5     .08       0
Bank Sta=530.5,555.5
XS Rating Curve= 0 ,0
Exp/Cntr=0.3,0.1

Type RM Length L Ch R = 1 ,2370.4  ,489.6,515.2,539.9
XS GIS Cut Line= 3
     1790353.539       97445.909      1790176.33       97911.361
     1789950.659       98373.692
#Sta/Elev= 30
      10  1776.1    39.8 1777.55    69.7 1775.35    89.6 1769.82   119.5 1766.16
   149.4 1757.64   159.4 1753.16   209.2  1743.4   219.1 1740.05   239.1 1723.33
     259 1721.49   268.9 1713.65   288.9 1707.62   308.8  1692.3   328.7 1687.61
   348.6 1673.58   398.4 1648.85   438.3  1635.2   478.1 1628.29   495.6 1620.48
   508.1 1618.12   520.6 1619.27   558.6 1628.88   598.9 1631.84   619.1 1639.26
   689.7 1675.12   780.5  1728.8     841 1756.44   931.8  1807.2  1012.5 1845.54
#Mann= 3 , 0 , 0
       0     .08       0   495.6    .045       0   520.6     .08       0
Bank Sta=495.6,520.6
XS Rating Curve= 0 ,0
Exp/Cntr=0.3,0.1

Type RM Length L Ch R = 1 ,1855.3  ,749.7,704.1,658.4
XS GIS Cut Line= 4
     1790087.303       97088.651      1790029.52       97577.757
     1789698.115       97651.402     1789412.548       97988.922
#Sta/Elev= 30
    10.1 1872.51    20.1 1871.05   110.6 1820.31   160.8 1805.79   231.2 1776.81
   261.3 1763.09   281.4 1747.02   301.5 1742.77   311.6 1731.39   331.7 1728.73
   381.9 1700.91     402 1699.66   412.1 1688.97   432.2 1688.12   482.5 1660.66
   512.5 1652.18   552.4 1631.78   582.4 1623.14   739.6 1609.43   752.1 1608.75
   756.8 1612.46   772.1  1628.6     802 1647.82   882.2 1662.34   902.3 1675.16
   952.6 1689.29  1053.1 1707.61  1133.4 1733.29  1183.7 1740.82  1274.1 1778.19
#Mann= 3 , 0 , 0
    10.1     .08       0   739.6    .045       0   756.8     .08       0
Bank Sta=739.6,756.8
XS Rating Curve= 0 ,0
Exp/Cntr=0.3,0.1

Type RM Length L Ch R = 1 ,1151.2  ,301.4,337.3,372.7
XS GIS Cut Line= 4
     1789267.515       96886.357     1789239.309       97261.651
     1789371.971       97714.527     1789263.414       97960.386
#Sta/Elev= 30
     9.9 1821.74    59.4 1805.04   128.8 1766.73   148.6 1747.03   168.4 1743.66
   178.3 1729.15   198.1 1723.99   217.9 1704.59   237.7 1700.34   247.6 1684.28
   267.4  1683.8   277.3 1669.65   297.1    1664   386.4 1607.64  519.59 1595.37
     527 1592.79   539.5 1592.88   687.6 1603.96   697.7 1618.17   717.7 1622.24
   737.8 1643.22   757.9 1648.14   767.9 1662.55     788 1665.35   808.1 1685.71
   858.2 1710.18   878.1    1729     898 1729.33   927.9  1751.3    1117 1847.98
#Mann= 3 , 0 , 0
     9.9     .06       0  519.59    .045       0   539.5     .06       0
Bank Sta=519.59,539.5
XS Rating Curve= 0 ,0
Exp/Cntr=0.3,0.1

Type RM Length L Ch R = 1 ,813.9   ,298.1,289.1,280.4
XS GIS Cut Line= 4
     1789246.212       96874.563     1789086.593       97359.259
      1788952.28       97450.748     1788843.272       97723.268
#Sta/Elev= 30
      10 1823.21      30 1807.41      50 1803.19      60 1791.57      80 1786.96
   100.1 1768.95   150.1 1750.57   200.1 1711.91   220.1 1707.67   240.1 1690.34
   260.2 1685.75   270.2 1673.36   290.2 1668.78   380.2 1616.56   400.2 1616.14
   420.2 1603.32   574.3 1587.34   586.8 1585.27   599.3 1586.97   634.6 1598.71
   644.1 1612.57   721.7 1647.52   731.5 1659.36   770.7 1683.13   790.2  1686.5
   839.1 1718.36   858.7 1721.98   917.4 1757.49     937 1761.22   966.3 1794.19
#Mann= 3 , 0 , 0
       0     .08       0   574.3    .045       0   599.3     .08       0
Bank Sta=574.3,599.3
XS Rating Curve= 0 ,0
Exp/Cntr=0.3,0.1