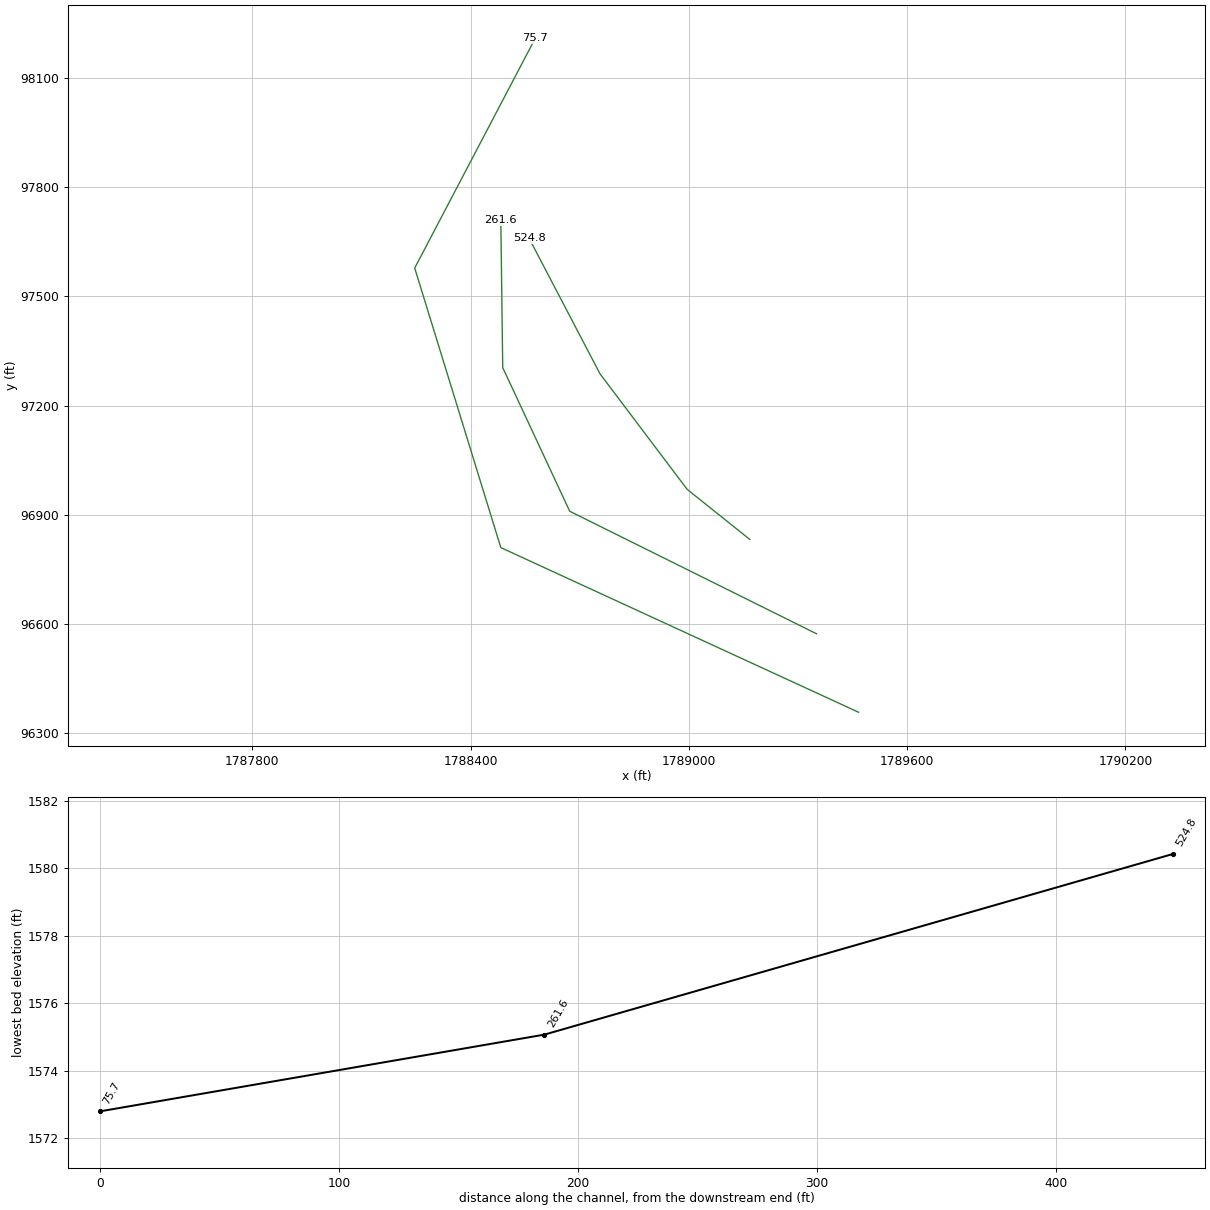
HEC-RAS study Cucumber Creek.prj: Cucumber Creek

--- Cucumber Creek.g01 (geometry) --- (continued)

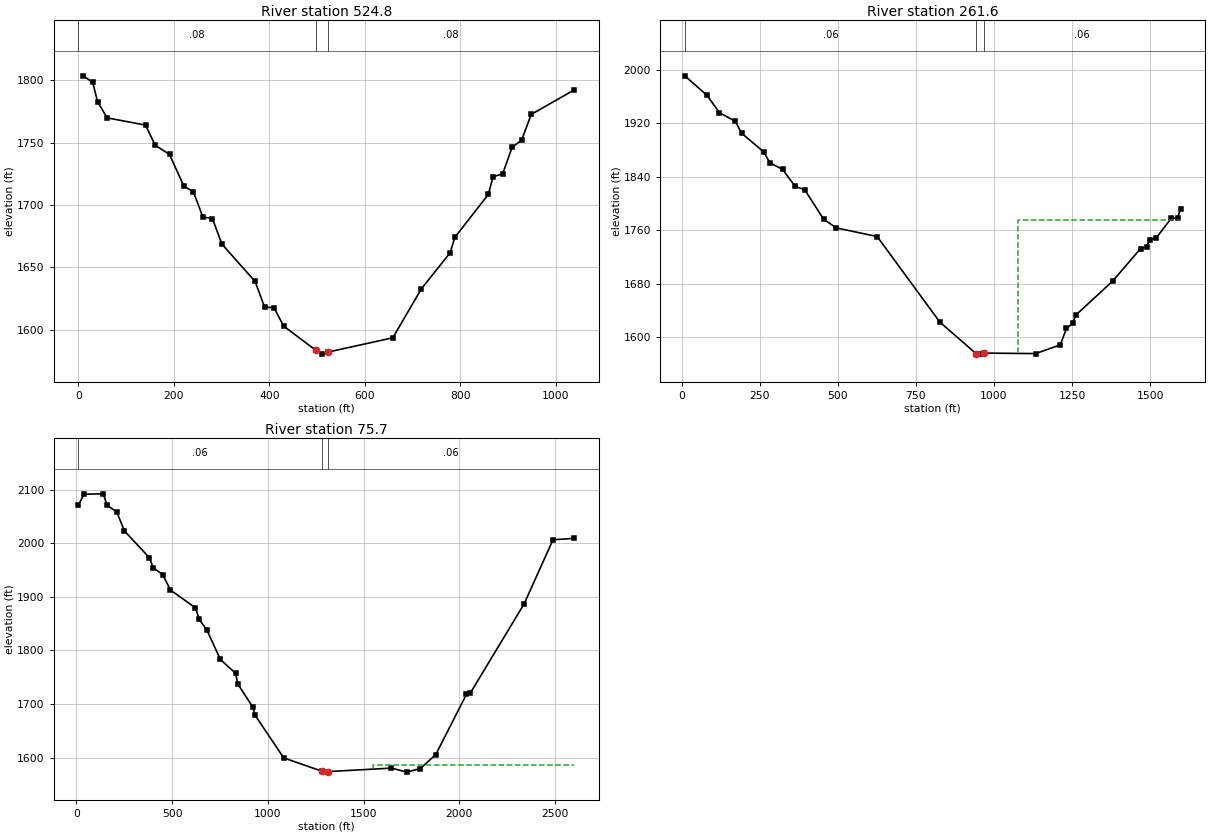
Type RM Length L Ch R = 1 ,524.8   ,268.9,263.2,257.4
XS GIS Cut Line= 4
     1789167.733       96831.992     1788995.028       96969.999
     1788755.599        97287.29     1788560.942       97659.085
#Sta/Elev= 30
      10  1803.5    30.1 1798.32    40.2 1782.85    60.3  1769.8   140.7 1764.03
   160.8 1747.96   190.9 1740.47   221.1 1714.96   240.9 1710.62   260.8 1690.31
   280.7 1689.12   300.6 1668.65   370.1 1638.68     390 1618.15   409.9 1617.57
   429.8  1602.9   496.8 1583.66   509.3 1580.42   521.8    1582   658.5 1593.51
   718.5 1632.91   778.4 1661.59   788.4 1674.07   858.4 1708.38   868.4 1722.57
   888.4 1724.96   908.3 1746.15   928.3 1752.08   948.3 1772.56  1038.2 1792.19
#Mann= 3 , 0 , 0
       0     .08       0   496.8    .045       0   521.8     .08       0
Bank Sta=496.8,521.8
XS Rating Curve= 0 ,0
Exp/Cntr=0.3,0.1

Type RM Length L Ch R = 1 ,261.6   ,189.9,185.9,181.9
XS GIS Cut Line= 4
     1789350.929       96573.022     1788672.339       96909.687
     1788488.225       97304.216     1788482.965       97709.266
#Sta/Elev= 30
    10.1 1991.03    80.8 1962.06   121.2 1935.92   171.7 1923.07   191.9 1905.36
   262.6 1877.37   282.8 1861.05   323.2 1851.19   363.6 1825.66   393.9 1820.96
   454.5 1776.81   494.9 1763.78   626.2  1750.8   826.8 1623.01   942.9 1575.85
   955.4 1575.07   967.9 1576.61  1133.5 1575.88  1212.6 1588.86  1232.4 1613.51
  1252.2 1620.93  1262.1 1633.26  1380.6 1684.36  1469.5 1732.73  1489.3 1735.67
  1499.2 1746.32  1518.9 1748.31  1568.3 1778.14  1588.1 1778.64    1598 1792.44
#Mann= 3 , 0 , 0
    10.1     .06       0   942.9    .045       0   967.9     .06       0
#XS Ineff= 2 , 0
                         1078.22         1774.91
Permanent Ineff=
       F       F
Bank Sta=942.9,967.9
XS Rating Curve= 0 ,0
Exp/Cntr=0.3,0.1

Type RM Length L Ch R = 1 ,75.7    ,68.3,75.7,83.2
XS GIS Cut Line= 4
     1789466.658       96357.346     1788482.965       96809.739
     1788246.247       97577.757     1788577.652       98209.004
#Sta/Elev= 30
      10 2071.54    40.1 2091.78   140.4 2092.53   160.4 2070.95   210.5 2058.88
   250.6 2023.25     381 1973.32     401 1954.47   451.1 1941.61   491.2 1912.77
   621.6 1879.69   641.6 1857.85   681.7 1837.93   751.9 1783.17   832.1    1757
   842.1 1737.73   922.3 1693.61   932.4 1679.42  1082.7 1599.37  1283.7 1574.29
  1313.8  1573.8  1645.3  1580.3  1725.7  1572.8    1796 1579.46  1876.4 1605.55
    2037 1718.17  2057.1 1720.43  2338.3 1887.18  2488.9 2006.79  2599.4 2009.29
#Mann= 3 , 0 , 0
      10     .06       0  1283.7    .045       0  1313.8     .06       0
#XS Ineff= 2 , 0
                         1550.05         1585.34
Permanent Ineff=
       F       F
Bank Sta=1283.7,1313.8
XS Rating Curve= 0 ,0
Exp/Cntr=0.3,0.1

Chan Stop Cuts=-1
Use User Specified Reach Order=0